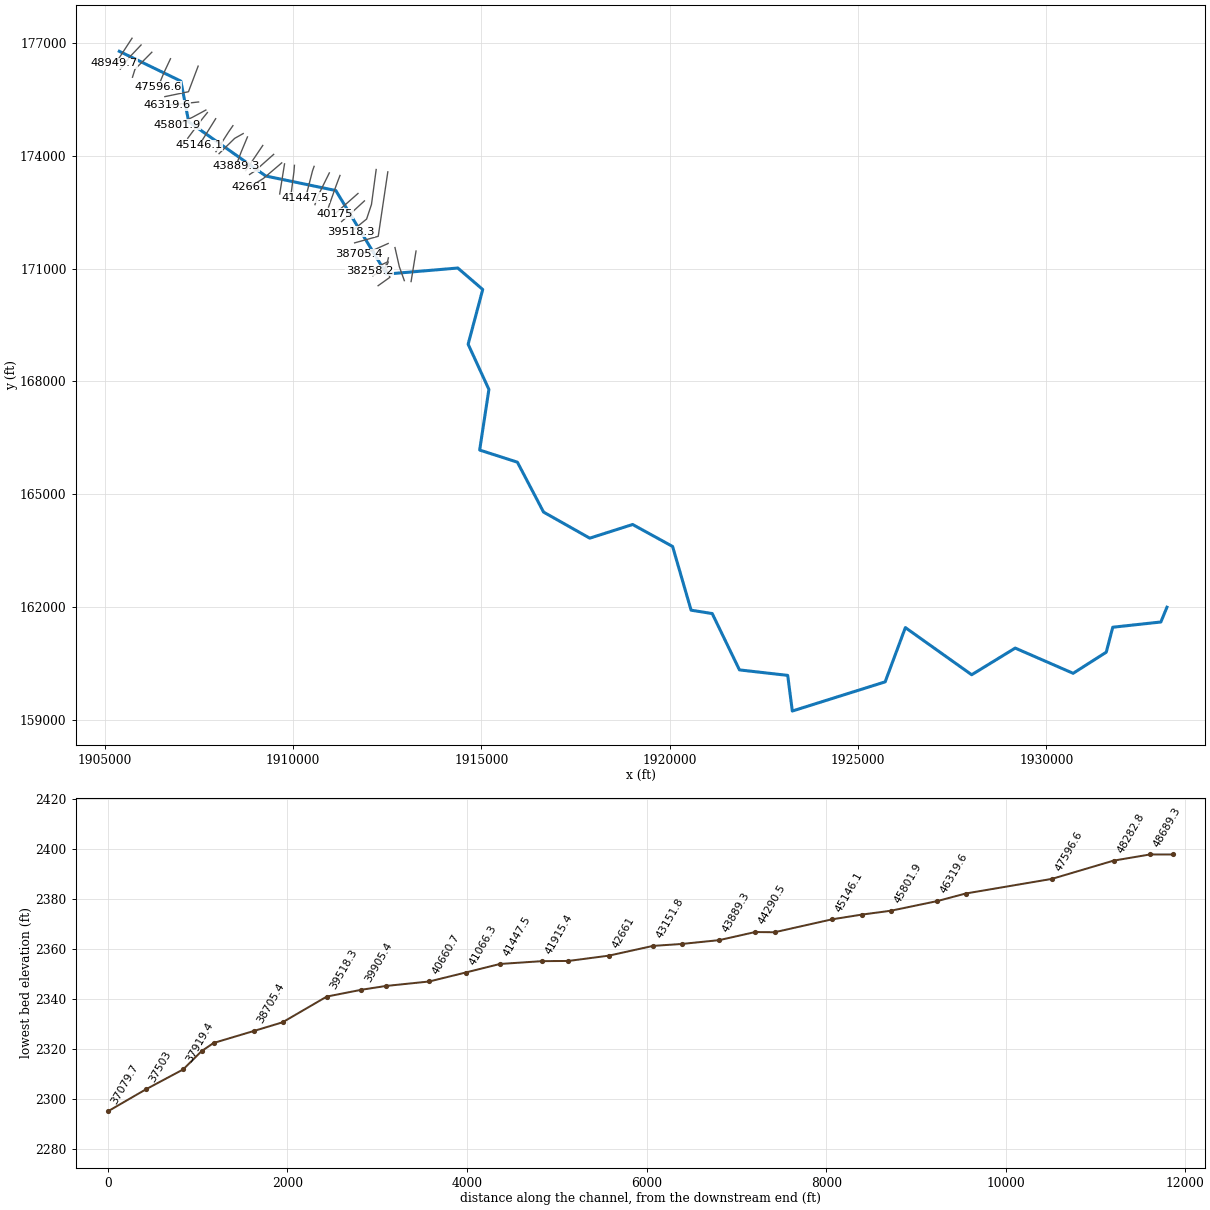
--- RchCrk.prj (project) ---

Proj Title=RchCrk
Current Plan=p01
Default Exp/Contr=0,0
English Units
Geom File=g01
Flow File=f01
Plan File=p01
BEGIN DESCRIPTION:
END DESCRIPTION:
DSS Export Rating Curves= 0
DSS Export Rating Curve Sorted= 0
DSS Export Volume Flow Curves= 0
DXF OffsetX= 0
DXF OffsetY= 0
DXF ScaleX= 0
DXF ScaleY= 0

--- RchCrk.p01 (plan) ---

Plan Title=Floodplain
Program Version=4.00
Geom File=g01
Flow File=f01
K Sum by GR=0
Std Step Tol=0.01
Critical Tol=0.01
Num of Std Step Trials=20
Max Error Tol=0.3
Flow Tol Ratio=0.001
Split Flow NTrial=30
Split Flow Tol=0.02
Split Flow Ratio=0.02
Log Output Level=0
Friction Slope Method=1
Unsteady Friction Slope Method=2
Unsteady Bridges Friction Slope Method=1
Global Log Level=0
CheckData=False
Run HTab=0
Run UNet=0
Run PostProcess=0
UNET Theta=0
UNET Theta Warmup=0
UNET ZTol=0
UNET ZSATol=0
UNET MxIter=0
UNET MaxInSteps=0
UNET DtIC=0
UNET DtMin=0
UNET MaxCRTS=0
UNET WFStab=0
UNET SFStab=0
UNET WFX=0
UNET SFX=0
UNET DSS MLevel=0
UNET DZMax Abort=0
UNET Convert EG Bridges=0
UNET Use Existing IB Tables=0
UNET Froude Limit=0
UNET Froude Power=0
Write IC File=0
Echo Input=False
Echo Output=False
Write Detailed=0

--- RchCrk.f01 (steady flow) ---

Flow Title=NFF Regression Equation
Program Version=4.00
Number of Profiles=1
Profile Names=P100yr
River Rch & RM=RchCrk,Main      ,48949.7
549.9452
River Rch & RM=RchCrk,Main      ,46633.8
604.2845
River Rch & RM=RchCrk,Main      ,44290.5
637.8743
River Rch & RM=RchCrk,Main      ,43889.3
722.8619
River Rch & RM=RchCrk,Main      ,42661
758.7845
River Rch & RM=RchCrk,Main      ,42210.6
845.8977
River Rch & RM=RchCrk,Main      ,39026.1
1444.063
River Rch & RM=RchCrk,Main      ,39026.1
889.5153
River Rch & RM=RchCrk,Main      ,36742.8
1542.444
River Rch & RM=RchCrk,Main      ,32189.3
1702.532
River Rch & RM=RchCrk,Main      ,27621.7
1885.927
River Rch & RM=RchCrk,Main      ,27096.4
2747.033
River Rch & RM=RchCrk,Main      ,20002.4
2950.906
River Rch & RM=RchCrk,Main      ,12222.7
3261.420
River Rch & RM=RchCrk,Main      ,679.3
3622.029
Boundary for River Rch & Prof#=RchCrk,Main      ,1
Up Type=0
Dn Type=3
Dn Slope=0.002033

--- RchCrk.g01 (geometry) ---

Geom Title=USGS 3m DEM
Program Version=4.10

River Reach=RchCrk          ,Main
Reach XY= 30
     1905388.945      176769.467     1907023.059      175977.801
     1907230.091      174898.374     1909278.268      173456.967
     1911136.228      173071.811     1912483.997      170852.801
     1914374.482      171013.723     1915036.677      170443.629
     1914649.471      168989.986     1915200.674      167789.249
      1914955.37      166179.091       1915957.1      165856.924
     1916651.908      164531.005     1917878.528      163838.478
     1919016.549      164201.759     1920077.747      163618.426
     1920568.632      161925.717      1921129.83      161835.873
     1921852.486       160339.78     1923133.736      160193.946
     1923256.132      159247.332     1925720.976      160022.071
     1926257.434      161463.478     1928017.851      160210.873
     1929174.101      160919.207     1930711.851      160249.237
     1931591.023      160810.001     1931763.501      161472.982
     1933040.459      161612.139     1933202.135      162004.446

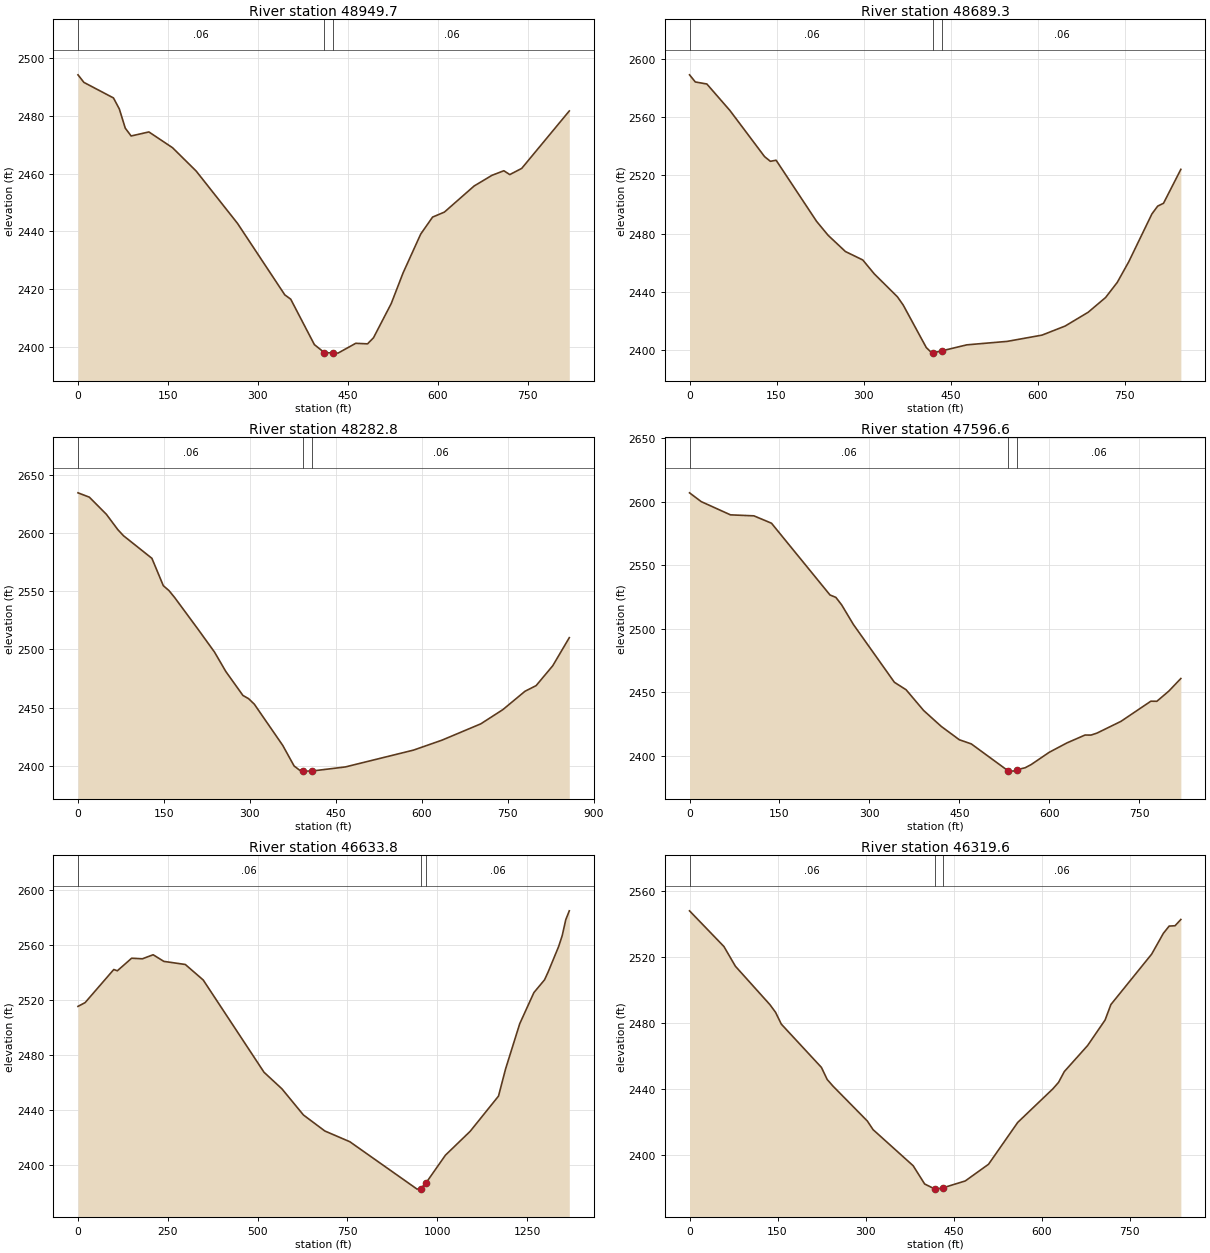
Type RM Length L Ch R = 1 ,48949.7 ,261,260,271.6
XS GIS Cut Line= 3
     1905726.195      177117.116     1905386.825      176596.869
     1905254.434      176448.902
#Sta/Elev= 30
       0 2494.19     9.9 2491.57    59.2 2486.19      69 2482.37    78.9 2475.73
    88.7 2473.03   118.3 2474.43   157.8 2468.96   197.2 2460.89   266.2 2442.77
   345.1 2418.04   354.9 2416.56   394.4 2400.84   411.2 2398.04   426.2 2397.96
   433.8 2397.89   463.4 2401.29   483.1  2401.1     493  2403.2   522.6 2415.04
   542.3 2425.61   571.8 2439.09   591.6 2444.96   611.3 2446.69   660.9 2455.72
   690.6 2459.41   710.5    2461   720.4 2459.67   740.3 2461.81   819.7 2481.69
#Mann= 3 , 0 , 0
       0     .06       0   411.2    .045       0   426.2     .06       0
Bank Sta=411.2,426.2
XS Rating Curve= 0 ,0
Exp/Cntr=0.3,0.1

Type RM Length L Ch R = 1 ,48689.3 ,405,406.4,403.9
XS GIS Cut Line= 3
      1905966.26      176937.947     1905672.049       176626.98
     1905415.198      176295.897
#Sta/Elev= 30
       0 2588.99      10 2584.09    29.9 2582.69    69.7 2564.48   129.4 2532.83
   139.4 2529.61   149.3 2530.35     219 2488.43   238.9 2478.83   268.8 2467.66
   298.7 2461.88   318.6  2452.3   358.4  2436.6   368.4 2430.93   408.2 2401.74
   418.1 2397.91   420.6 2398.12   435.6 2399.53     478 2403.59   547.8 2405.98
   607.7 2410.27   647.6  2416.5   687.5 2426.02   717.4 2436.12   737.4 2446.44
   757.3 2460.66   797.2 2493.48   807.2 2498.86   817.2  2500.8   847.1 2524.09
#Mann= 3 , 0 , 0
       0     .06       0   420.6    .045       0   435.6     .06       0
Bank Sta=420.6,435.6
XS Rating Curve= 0 ,0
Exp/Cntr=0.3,0.1

Type RM Length L Ch R = 1 ,48282.8 ,677.5,686.2,695
XS GIS Cut Line= 3
     1906251.262      176744.836     1905804.766      176293.148
     1905738.324      176081.107
#Sta/Elev= 30
       0 2634.48    19.8 2630.76    49.6 2616.01    69.5 2602.88    79.4 2597.63
     129 2578.21   148.9 2554.72   158.8  2550.5   168.7 2544.54   208.4 2518.04
   238.2 2497.72     258 2480.98   287.8 2460.46   297.7 2457.67   307.6 2453.01
   357.3 2417.53   377.1 2399.88     387 2396.14   393.3  2395.7     397 2395.44
   408.3 2395.53   466.4 2399.02   585.5  2413.5   635.1 2422.03   702.8 2436.04
   741.4 2448.28     780 2464.04   799.4 2468.88   828.4 2485.95   857.3 2510.08
#Mann= 3 , 0 , 0
       0     .06       0   393.3    .045       0   408.3     .06       0
Bank Sta=393.3,408.3
XS Rating Curve= 0 ,0
Exp/Cntr=0.3,0.1

Type RM Length L Ch R = 1 ,47596.6 ,967.3,962.3,937.1
XS GIS Cut Line= 3
     1906747.349       176572.62     1906573.144      176201.405
     1906416.962      175822.965
#Sta/Elev= 30
       0  2606.9    19.5 2599.99    68.3 2589.59   107.4 2588.81   136.7 2583.02
   234.3 2526.61   244.1 2524.72   253.8 2518.78   273.4 2503.37   341.7 2457.98
   361.2 2452.12   390.5 2435.79     420 2423.25     450 2412.81     470 2409.54
   530.7 2388.61   539.9 2388.14   545.7 2389.22   559.8 2390.79   569.8 2393.28
   599.8  2402.9   629.7 2410.36   659.7 2416.51   669.7 2416.48   679.7 2418.05
   719.6 2427.26   769.5 2443.11   779.5 2443.04   799.5 2451.07   819.5 2460.95
#Mann= 3 , 0 , 0
       0     .06       0   530.7    .045       0   545.7     .06       0
Bank Sta=530.7,545.7
XS Rating Curve= 0 ,0
Exp/Cntr=0.3,0.1

Type RM Length L Ch R = 1 ,46633.8 ,315.8,314,312
XS GIS Cut Line= 3
     1907481.723      176376.217     1907224.728      175696.089
     1906597.601      175565.688
#Sta/Elev= 30
       0 2515.12    19.9 2517.86    99.6 2541.91   109.6    2541   149.4 2550.13
   179.3 2549.71   209.2 2552.65     239 2547.83   298.8 2545.57   348.6  2534.3
   517.9 2467.21   567.7 2455.18   627.5 2436.18   687.2 2424.52   756.6 2416.74
   943.9 2382.27   953.7 2382.65   968.7 2386.76  1022.7 2406.91  1091.7 2424.31
  1170.5 2449.89  1190.2 2469.63  1229.6 2502.51  1269.1 2525.16  1298.6  2534.4
  1308.5    2540    1338 2558.68  1347.9 2566.61  1357.8 2578.15  1367.6 2584.58
#Mann= 3 , 0 , 0
       0     .06       0   953.7    .045       0   968.7     .06       0
Bank Sta=953.7,968.7
XS Rating Curve= 0 ,0
Exp/Cntr=0.3,0.1

Type RM Length L Ch R = 1 ,46319.6 ,507.1,517.4,525.4
XS GIS Cut Line= 3
      1907492.94       175424.02      1907075.17      175378.109
     1906660.119      175337.834
#Sta/Elev= 30
       0 2548.02    58.6 2526.39    78.2 2514.41   136.8 2491.22   146.6  2486.5
   156.4 2479.33   224.8 2453.06   234.6 2445.74   244.4 2441.76     303 2420.57
   312.8 2415.33   381.2 2393.42   400.7 2382.38   417.5 2379.43   420.3 2379.26
   432.5 2380.11   469.9 2384.22   509.6 2394.35   559.3 2419.71   618.9 2439.96
   628.8 2443.96   638.7 2450.54   678.4 2466.33   708.2 2481.81   718.1  2491.2
   787.6 2521.78   807.5 2534.36   817.4 2538.77   827.4 2538.97   837.3 2542.77
#Mann= 3 , 0 , 0
       0     .06       0   417.5    .045       0   432.5     .06       0
Bank Sta=417.5,432.5
XS Rating Curve= 0 ,0
Exp/Cntr=0.3,0.1

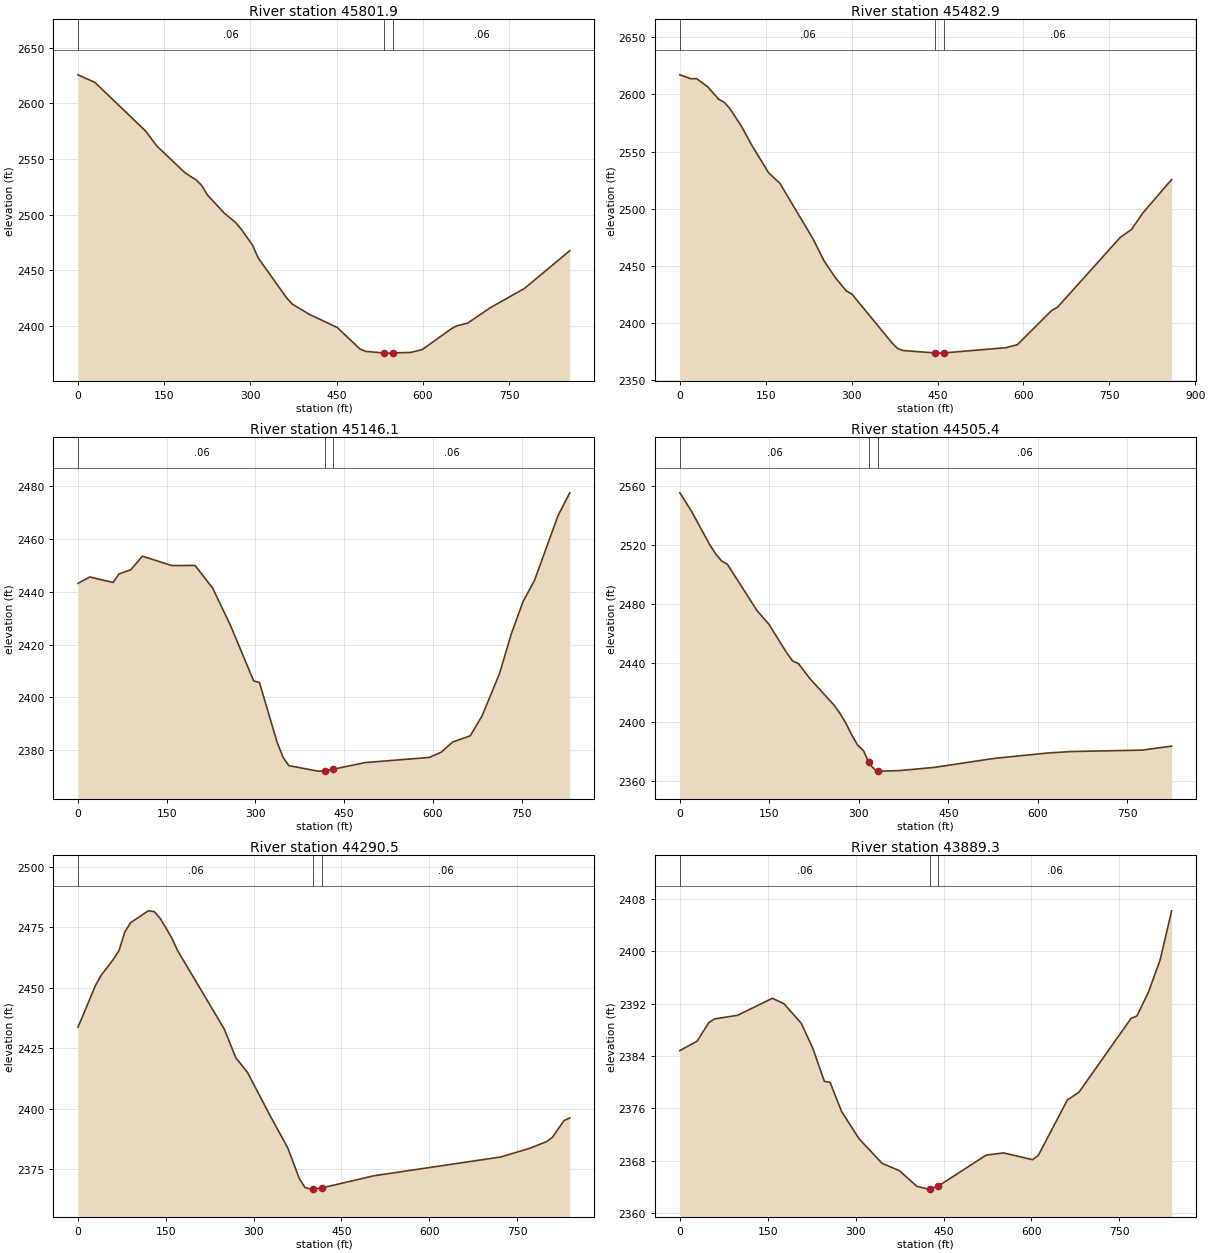
Type RM Length L Ch R = 1 ,45801.9 ,309.6,319,329.3
XS GIS Cut Line= 3
     1907686.491      175209.432     1907332.994      175018.608
     1906922.791      174824.737
#Sta/Elev= 30
       0 2625.77    29.4 2618.97   117.6 2575.21   137.2 2561.68   186.2 2537.61
   205.8 2531.13   215.6 2525.94   225.4 2517.53   254.8 2501.16   274.3 2492.82
   284.1 2486.77   303.7 2472.46   313.5    2461   362.5 2425.38   372.3 2419.73
   401.7 2410.45     451 2398.43   490.5  2379.1   500.4 2376.97     533 2375.46
   539.8 2375.39     548 2375.54   579.2 2376.06     599 2378.63   648.3 2396.94
   658.2 2399.83   677.9 2402.42   717.3 2416.29   776.5 2433.54   855.4 2467.52
#Mann= 3 , 0 , 0
       0     .06       0     533    .045       0     548     .06       0
Bank Sta=533,548
XS Rating Curve= 0 ,0
Exp/Cntr=0.3,0.1

Type RM Length L Ch R = 1 ,45482.9 ,332.5,336.8,339.4
XS GIS Cut Line= 3
     1907727.036      175142.836     1907532.343      174901.417
     1907205.769      174460.426
#Sta/Elev= 30
       0 2617.04    19.4 2613.62    29.1 2613.76    48.5 2606.65    67.8 2595.67
    77.5 2593.07    87.2 2587.64   106.6 2572.93     126 2555.19   155.1 2531.37
   174.5 2522.37   232.6 2473.72     252 2454.35   271.4 2439.95   290.8 2428.14
   300.4 2425.53     370 2383.13     380 2377.98     390 2376.14   445.5 2374.05
   449.8 2373.87   460.5 2374.02   569.6 2378.62   589.5 2381.26   649.4 2411.16
   659.4 2413.87   769.1 2474.98     789 2482.01     809 2496.59   858.9 2525.57
#Mann= 3 , 0 , 0
       0     .06       0   445.5    .045       0   460.5     .06       0
Bank Sta=445.5,460.5
XS Rating Curve= 0 ,0
Exp/Cntr=0.3,0.1

Type RM Length L Ch R = 1 ,45146.1 ,557.9,639.7,640.2
XS GIS Cut Line= 2
     1907947.035      174979.702     1907507.051      174274.191
#Sta/Elev= 30
       0 2443.21    19.8 2445.63    59.4 2443.56    69.3 2446.79    89.1 2448.34
   108.9 2453.53   158.4 2449.98     198    2450   227.7 2441.39   257.4 2427.47
     297 2406.21   306.8 2405.56   336.5 2383.03   346.4 2377.33   356.3 2374.05
   405.8 2371.95     417 2372.02     432 2372.69     485 2375.18   593.9 2377.15
   613.7 2379.07   633.5 2382.99   663.2 2385.36     683  2392.8   712.7 2408.96
   732.5 2423.92   752.3 2436.18   772.1 2444.47   811.7 2468.94   831.5 2477.57
#Mann= 3 , 0 , 0
       0     .06       0     417    .045       0     432     .06       0
Bank Sta=417,432
XS Rating Curve= 0 ,0
Exp/Cntr=0.3,0.1

Type RM Length L Ch R = 1 ,44505.4 ,221.2,214.9,208.7
XS GIS Cut Line= 3
     1908404.568      174794.335     1908291.646      174630.793
     1907954.059      174104.177
#Sta/Elev= 30
       0 2555.19    19.9 2542.45    49.7 2520.32    59.6 2514.11    69.6 2509.16
    79.5 2506.89   129.2 2475.53     149 2466.36   178.9 2447.04   188.8 2441.41
   198.7 2439.58   218.6 2429.13   258.3 2411.56   268.2 2405.96   278.2 2399.27
   288.1 2391.26     298 2384.37     308 2380.52   316.6 2372.69   317.9 2371.51
   327.8 2367.42   331.6 2367.18   337.8 2366.78   367.5 2367.13   427.1 2369.34
   526.4 2375.37   615.8 2379.02   655.5 2380.04   774.6    2381   824.3  2383.7
#Mann= 3 , 0 , 0
       0     .06       0   316.6    .045       0   331.6     .06       0
Bank Sta=316.6,331.6
XS Rating Curve= 0 ,0
Exp/Cntr=0.3,0.1

Type RM Length L Ch R = 1 ,44290.5 ,390.9,401,411.8
XS GIS Cut Line= 3
     1908677.741      174585.037     1908451.295      174457.516
     1908037.025      174051.517
#Sta/Elev= 30
       0 2433.71      30 2451.05      40 2455.28      60 2461.59      70 2465.33
      80 2473.06      90 2476.88     120 2481.75   129.9 2481.46   139.9 2478.78
   149.9 2474.82   159.9 2470.66   169.9 2465.43   249.9  2432.9   269.7 2421.01
   289.4  2415.1   328.7 2396.92   358.2 2383.96   377.9 2371.26   387.7 2367.54
   397.5 2366.87   401.5 2366.93   416.5 2367.37   505.7  2372.4     722 2380.14
   771.1 2383.69   800.6 2386.51   810.4  2388.3   830.1 2395.17   839.9 2396.25
#Mann= 3 , 0 , 0
       0     .06       0   401.5    .045       0   416.5     .06       0
Bank Sta=401.5,416.5
XS Rating Curve= 0 ,0
Exp/Cntr=0.3,0.1

Type RM Length L Ch R = 1 ,43889.3 ,417.8,416.2,412.5
XS GIS Cut Line= 3
     1908790.445      174495.072     1908623.615      174094.484
     1908480.819      173715.085
#Sta/Elev= 30
       0 2384.82    29.6 2386.28    49.3 2389.09    59.2 2389.67    98.6 2390.22
   157.8 2392.82   177.5    2392   207.1 2389.01   226.8  2385.2   246.6 2380.12
   256.4 2379.95   276.1 2375.49   305.7 2371.35   345.2 2367.57   374.8 2366.45
   404.4 2364.06   424.1 2363.63   426.4 2363.66   441.4 2364.12   522.9 2368.84
   552.6 2369.17     602 2368.13   611.9 2368.81   661.4 2377.28   681.1 2378.45
   770.1 2389.75     780 2390.11   799.8 2393.78   819.6 2398.67   839.3  2406.2
#Mann= 3 , 0 , 0
       0     .06       0   426.4    .045       0   441.4     .06       0
Bank Sta=426.4,441.4
XS Rating Curve= 0 ,0
Exp/Cntr=0.3,0.1

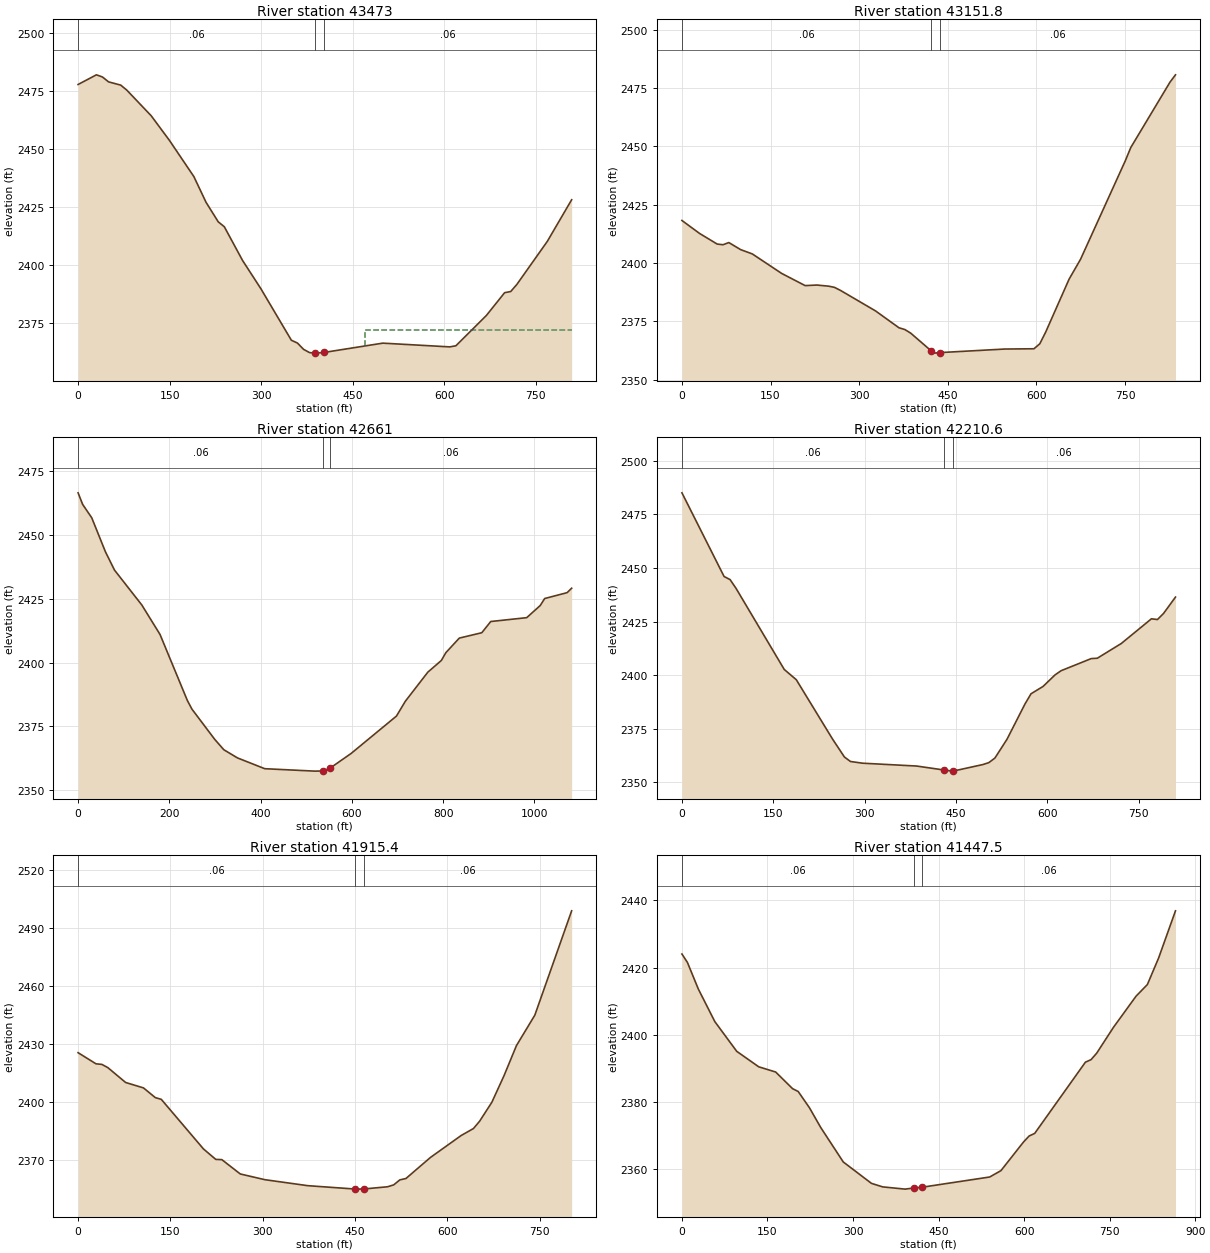
Type RM Length L Ch R = 1 ,43473   ,329.4,321.1,315.7
XS GIS Cut Line= 2
     1909196.969      174268.664     1908744.603      173598.449
#Sta/Elev= 30
       0 2477.85      30 2482.01    39.9 2481.09    49.9 2478.98    69.9 2477.57
    79.9  2475.4   119.8 2464.36   149.7 2453.75   189.7 2438.16   209.6  2427.1
   229.6 2418.68   239.6 2416.54   269.5 2402.01   299.5 2389.84   349.4 2367.66
   359.4 2366.44   369.4 2363.73   379.3 2362.32   387.8 2362.13   389.3  2362.1
   402.8 2362.39   499.1  2366.4   608.9 2364.79   618.9 2365.26   668.8 2378.29
   698.8 2388.14   708.8 2388.65   718.8 2391.68   768.7 2410.24   808.6 2428.18
#Mann= 3 , 0 , 0
       0     .06       0   387.8    .045       0   402.8     .06       0
#XS Ineff= 2 , 0
                           470.6         2372.01
Permanent Ineff=
       F       F
Bank Sta=387.8,402.8
XS Rating Curve= 0 ,0
Exp/Cntr=0.3,0.1

Type RM Length L Ch R = 1 ,43151.8 ,331,490.8,508
XS GIS Cut Line= 3
     1909486.552      174032.208     1908988.648      173591.132
     1908846.659      173497.599
#Sta/Elev= 30
       0 2418.21    29.8 2412.66    59.6  2408.1    69.5 2407.81    79.4 2408.74
    99.3 2405.72   119.1 2403.87   168.8  2395.5   208.5 2390.28   228.3 2390.52
   248.2 2390.04   258.1 2389.53   268.1 2388.25   327.6 2379.43   367.3 2372.19
   377.3 2371.43   387.2 2369.88   421.8  2362.3   426.9 2361.32   436.8 2361.55
     546 2363.07   595.7 2363.19   605.6 2365.34   615.5 2370.32   655.2 2393.06
   674.6  2401.6   750.2 2443.77   759.6 2449.52   825.8  2477.5   835.2 2480.68
#Mann= 3 , 0 , 0
       0     .06       0   421.8    .045       0   436.8     .06       0
#XS Ineff= 2 , 0
                          575.77         2363.09
Permanent Ineff=
       F       F
Bank Sta=421.8,436.8
XS Rating Curve= 0 ,0
Exp/Cntr=0.3,0.1

Type RM Length L Ch R = 1 ,42661   ,596.2,450.4,467.3
XS GIS Cut Line= 3
     1909700.775      173806.449     1909214.492      173392.545
     1908836.787       173160.86
#Sta/Elev= 30
       0 2466.51      10 2461.97    29.9 2456.74    59.9 2443.41    79.8 2436.23
   139.7 2422.54   179.6 2410.99   239.5 2385.11   249.4 2381.76   299.3 2369.92
   319.3 2365.83   349.2 2362.62   409.1 2358.38   518.8 2357.43   537.1 2357.49
   552.1 2358.58   598.7  2364.4   697.7    2379   717.4 2384.86   766.6 2396.24
   796.1 2400.79     806 2403.86   835.5 2409.57   884.8 2411.68   904.4 2416.07
   983.2 2417.58  1012.8 2422.33  1022.6 2425.08  1071.8 2427.39  1081.7 2429.12
#Mann= 3 , 0 , 0
       0     .06       0   537.1    .045       0   552.1     .06       0
Bank Sta=537.1,552.1
XS Rating Curve= 0 ,0
Exp/Cntr=0.3,0.1

Type RM Length L Ch R = 1 ,42210.6 ,293.5,295.3,297.1
XS GIS Cut Line= 2
     1909775.208      173779.984      1909646.71      172979.796
#Sta/Elev= 30
       0 2485.07    69.2 2446.06    79.1  2444.6      89 2440.45     168 2402.71
   187.8 2397.92   247.1 2370.35   266.8 2361.88   276.7  2359.8   296.5    2359
   385.4 2357.67   430.2 2355.83   444.8  2355.3   445.2 2355.31   494.2 2358.37
     504 2359.27   513.9  2361.4   533.7 2370.13   563.4 2386.68   573.2 2391.37
     593  2394.8   612.8 2400.21   622.7 2402.14   672.1 2407.78     682 2407.94
   721.5 2414.83   770.9 2426.33   780.8 2425.99   790.7 2428.79   810.4 2436.46
#Mann= 3 , 0 , 0
       0     .06       0   430.2    .045       0   445.2     .06       0
Bank Sta=430.2,445.2
XS Rating Curve= 0 ,0
Exp/Cntr=0.3,0.1

Type RM Length L Ch R = 1 ,41915.4 ,472.1,467.7,463.4
XS GIS Cut Line= 3
     1910038.043      173741.046     1910024.415      173567.769
     1909944.591      172944.751
#Sta/Elev= 30
       0 2425.57      29 2419.84    38.6 2419.53    48.3 2417.88    77.2 2410.21
   106.2 2407.42   125.5  2402.4   135.2  2401.5   203.7 2375.94   223.7 2370.55
   233.6 2370.42   263.5 2363.04   303.4 2360.09   373.2    2357   450.2 2355.26
     453 2355.22   465.2 2355.33   502.8 2356.44   512.8 2357.41   522.8 2359.99
   532.7  2360.7   572.6 2371.58   622.5 2382.89   642.4 2386.47   652.4 2390.25
   672.3 2400.03   692.2 2413.83   712.2 2429.21   742.1 2444.93   801.9 2498.71
#Mann= 3 , 0 , 0
       0     .06       0   450.2    .045       0   465.2     .06       0
Bank Sta=450.2,465.2
XS Rating Curve= 0 ,0
Exp/Cntr=0.3,0.1

Type RM Length L Ch R = 1 ,41447.5 ,384.9,381,377
XS GIS Cut Line= 3
     1910560.146      173713.556     1910518.297      173595.854
     1910333.977      172878.555
#Sta/Elev= 30
       0 2424.06     9.6 2421.56    28.8 2413.62    57.7 2403.94    96.1  2395.1
   134.8 2390.48   164.4 2388.94     194 2383.99   203.9 2383.14   223.7 2378.29
   243.4 2372.43   282.9 2362.18   332.3 2355.81     352 2354.76   391.5 2354.09
   406.7 2354.44   421.7 2354.67   539.7  2357.7   559.4 2359.59   598.9 2368.09
   608.8  2369.9   618.6 2370.67   707.5 2391.86   717.4 2392.62   727.3 2394.54
   756.9 2402.28   796.4 2411.52   816.2 2414.97   835.9 2422.86   865.5 2436.91
#Mann= 3 , 0 , 0
       0     .06       0   406.7    .045       0   421.7     .06       0
Bank Sta=406.7,421.7
XS Rating Curve= 0 ,0
Exp/Cntr=0.3,0.1

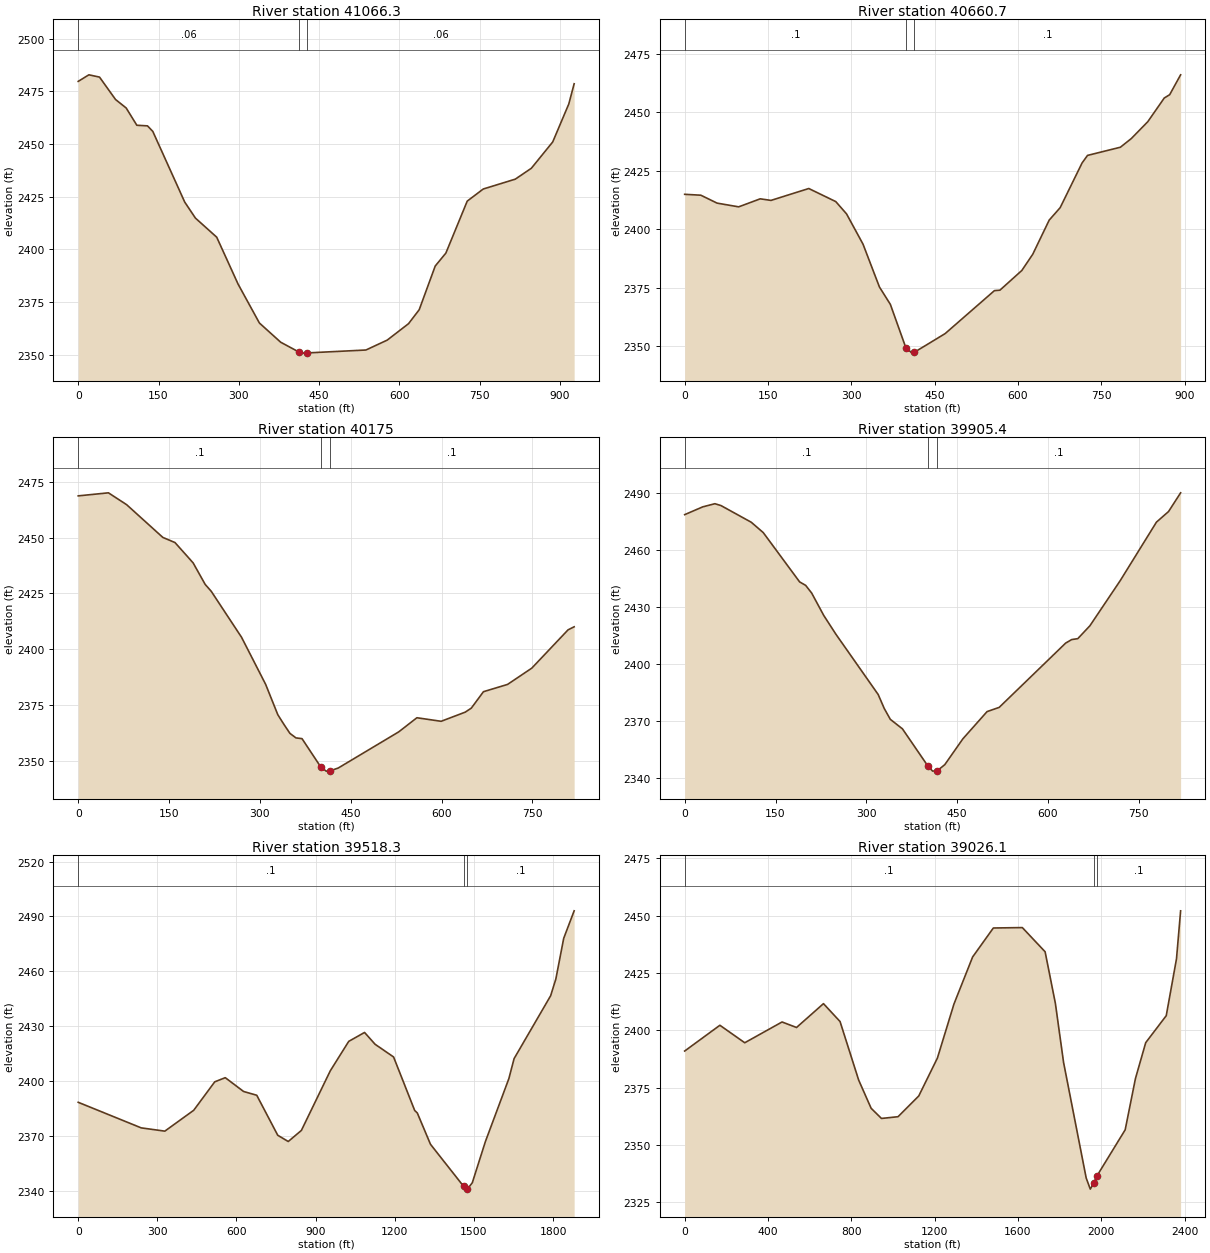
Type RM Length L Ch R = 1 ,41066.3 ,401.9,405.7,409.6
XS GIS Cut Line= 3
     1910964.433      173539.773     1910655.221      172915.547
     1910583.184      172697.491
#Sta/Elev= 30
       0  2479.8    19.9 2482.92    39.8 2481.84    69.7  2471.2    89.6 2467.16
   109.5 2458.95   129.4 2458.67   139.3 2456.04     199 2422.43   218.9 2414.85
   258.7 2405.77   298.6 2383.48   338.4    2365   378.2 2355.86   412.9 2351.12
     418 2350.68   427.9 2350.78   537.4 2352.16   577.2 2356.87     617 2364.68
   636.9 2371.31   666.8 2392.06   686.7 2398.21   726.6 2422.91   756.5 2428.66
   816.4 2433.35   846.4 2438.53   886.3 2451.03   916.3 2469.07   926.3 2478.67
#Mann= 3 , 0 , 0
       0     .06       0   412.9    .045       0   427.9     .06       0
Bank Sta=412.9,427.9
XS Rating Curve= 0 ,0
Exp/Cntr=0.3,0.1

Type RM Length L Ch R = 1 ,40660.7 ,497,485.4,473.9
XS GIS Cut Line= 3
     1911247.088      173472.369       1911143.9      173199.799
     1910943.372      172632.824
#Sta/Elev= 30
       0 2414.98    29.1  2414.6    58.3 2411.22    97.2 2409.62     136 2413.05
   155.4 2412.38   223.4 2417.46     272 2411.87   291.4 2406.61     321  2393.7
   350.6 2375.37   370.3 2367.92   398.4 2349.23   409.8 2347.09   413.4 2347.44
   468.9 2355.44   557.6  2373.8   567.5    2374   606.9 2382.41   626.6 2389.35
   656.2 2403.94     676 2409.29   715.4 2428.38   725.2 2431.61   784.4 2435.11
   804.1 2438.83   833.7 2446.02   863.3 2456.13   873.1 2457.57   892.8 2466.06
#Mann= 3 , 0 , 0
       0      .1       0   398.4    .045       0   413.4      .1       0
Bank Sta=398.4,413.4
XS Rating Curve= 0 ,0
Exp/Cntr=0.3,0.1

Type RM Length L Ch R = 1 ,40175   ,269.2,269.6,269.8
XS GIS Cut Line= 3
     1911725.338      172993.828     1911418.279      172722.894
      1911111.22       172451.96
#Sta/Elev= 30
       0 2468.73    49.9  2470.1    79.9  2464.8   139.8 2450.09   159.8  2447.8
   179.8 2441.73   189.8 2438.66   209.7 2429.02   219.7 2425.93   269.7 2405.33
   309.6 2384.16   329.6  2370.6   339.6 2366.29   349.6 2362.22   359.6 2360.18
   369.6 2359.85   400.6 2347.13   409.5 2345.28   415.6 2345.37   429.5 2346.68
   529.4  2362.9   559.3 2369.22   599.3 2367.63   639.2 2371.74   649.2 2373.54
   669.2  2380.9   709.1 2384.18   749.1 2391.48     809 2408.66     819 2410.01
#Mann= 3 , 0 , 0
       0      .1       0   400.6    .045       0   415.6      .1       0
Bank Sta=400.6,415.6
XS Rating Curve= 0 ,0
Exp/Cntr=0.3,0.1

Type RM Length L Ch R = 1 ,39905.4 ,388.4,387,386
XS GIS Cut Line= 3
     1911896.419      172796.523       1911594.9       172519.45
     1911289.363      172246.724
#Sta/Elev= 30
       0 2478.74      30 2482.85    49.9 2484.49    59.9 2483.52   109.9 2474.75
   129.8 2469.28   189.8 2443.36   199.8 2441.52   209.7  2437.5   229.7 2425.68
   249.7 2415.83   319.6 2384.08   329.6 2376.73   339.6 2371.03   359.6 2366.04
     402  2346.3   409.5 2343.78     417 2343.96   429.5 2347.16   459.4 2360.77
   499.4 2375.11   519.4 2377.32   629.2 2411.16   639.2 2413.01   649.2 2413.49
   669.2 2420.27   719.2 2443.98   779.1  2474.8   799.1 2480.38     819 2490.22
#Mann= 3 , 0 , 0
       0      .1       0     402    .045       0     417      .1       0
Bank Sta=402,417
XS Rating Curve= 0 ,0
Exp/Cntr=0.3,0.1

Type RM Length L Ch R = 1 ,39518.3 ,501.6,492.2,482.8
XS GIS Cut Line= 4
     1912208.059      173630.016     1912083.442      172702.801
     1911953.824      172313.945     1911539.261      171976.546
#Sta/Elev= 30
       0 2388.48   238.9  2374.5   328.4 2372.72   437.9 2384.12   517.5 2399.65
   557.4 2401.93     627 2394.38   676.8 2392.32   756.4 2370.47   796.2 2367.06
     846 2373.11   955.6 2405.68  1025.5 2421.76  1085.5 2426.63  1125.5 2420.17
  1195.5 2413.24  1275.5 2384.02  1285.5 2382.63  1335.4 2365.54  1460.6 2342.63
  1474.1 2341.04  1475.6 2341.11  1493.9 2344.52  1543.4 2366.96  1632.5  2401.4
  1652.3 2412.33  1790.9 2446.69  1810.7 2455.88  1840.4 2478.05    1880 2493.08
#Mann= 3 , 0 , 0
       0      .1       0  1460.6    .045       0  1475.6      .1       0
Bank Sta=1460.6,1475.6
XS Rating Curve= 0 ,0
Exp/Cntr=0.3,0.1

Type RM Length L Ch R = 1 ,39026.1 ,317.3,320.8,321
XS GIS Cut Line= 3
      1912517.14        173568.2     1912262.742      171856.361
     1911636.114      171681.719
#Sta/Elev= 30
       0 2390.99   169.1 2402.23   288.4  2394.6   467.5 2403.66   537.1 2401.26
   666.4 2411.66     746 2403.86   835.5  2378.3   895.2 2366.02   944.9 2361.58
  1024.5 2362.34  1123.9 2371.39  1213.4 2387.91    1293 2411.51  1382.5 2432.01
    1482 2444.66  1621.2 2444.84  1730.6 2434.29  1779.9 2411.78  1819.3 2385.99
  1927.8 2335.61  1947.5 2330.75  1963.2 2333.23  1978.2 2336.32    2115 2356.62
  2164.3 2378.98  2213.6 2394.64  2312.2 2406.41  2361.4  2431.2  2381.2 2452.15
#Mann= 3 , 0 , 0
       0      .1       0  1963.2    .045       0  1978.2      .1       0
Bank Sta=1963.2,1978.2
XS Rating Curve= 0 ,0
Exp/Cntr=0.3,0.1

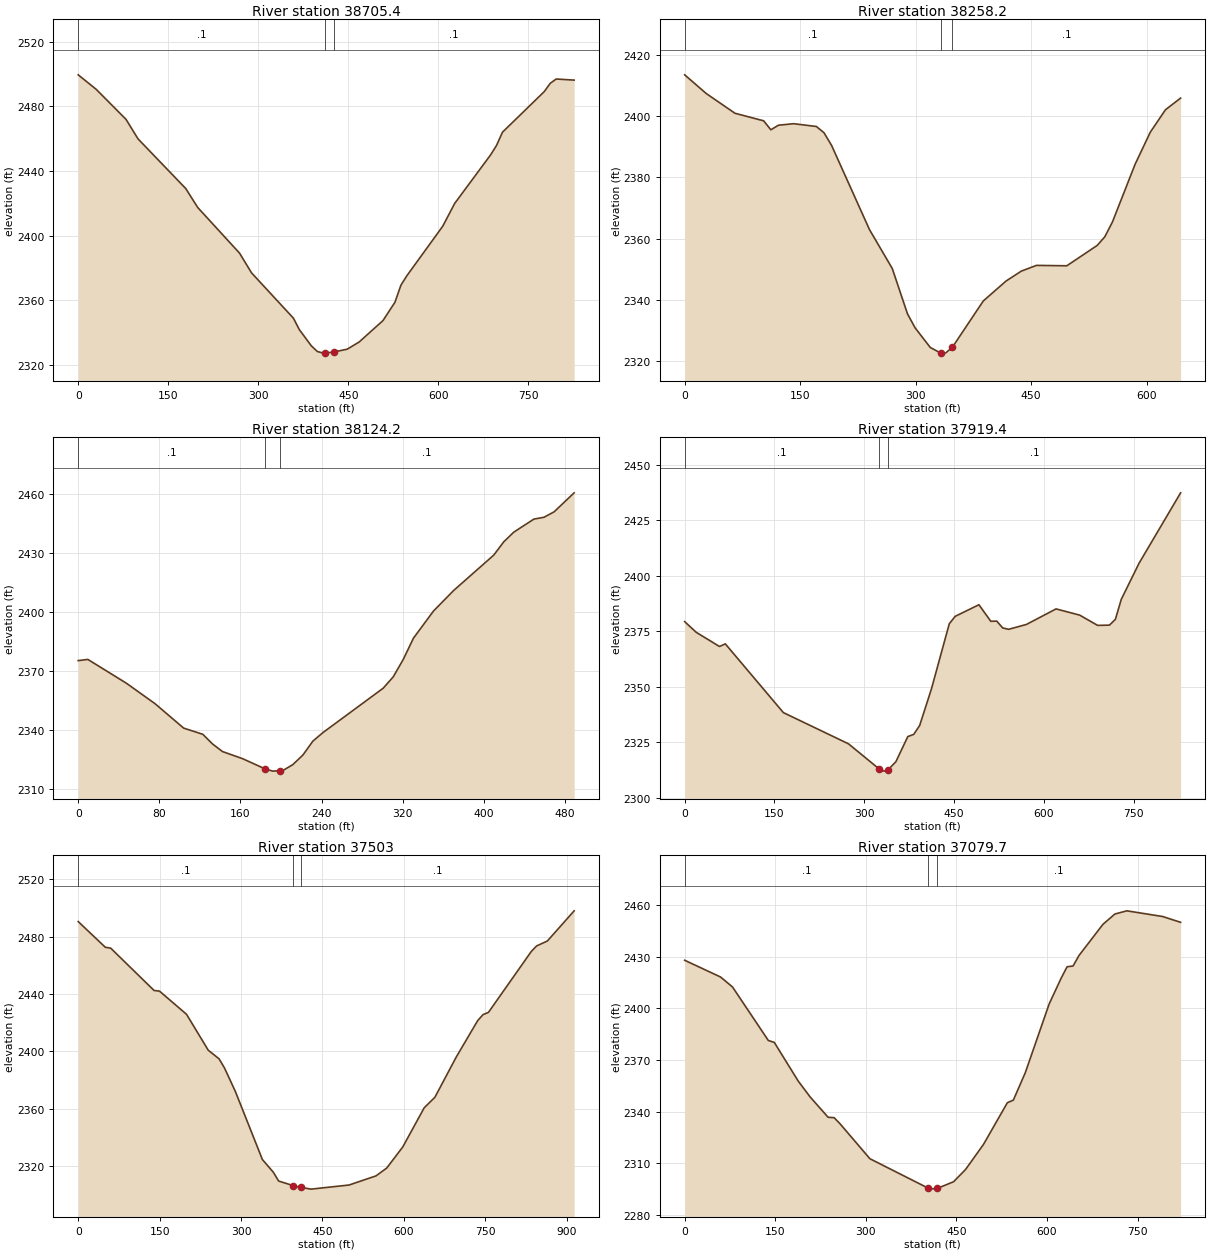
Type RM Length L Ch R = 1 ,38705.4 ,446.5,446.9,450.6
XS GIS Cut Line= 3
     1912526.392      171665.479     1912144.886      171494.132
     1911752.831      171381.326
#Sta/Elev= 30
       0 2499.48    29.9 2490.53    79.7 2471.91    99.6 2459.87   179.2 2429.09
   199.2 2417.35   268.8 2389.13   288.8 2376.92   358.5 2348.91   368.4  2341.8
   388.4 2331.76   398.3  2328.3   408.3 2327.27   410.7 2327.32   425.7 2327.95
   448.1 2329.71     468 2334.15   507.8 2347.44   527.7 2358.78   537.6 2369.32
   547.6  2375.2   607.3 2405.81   627.2 2419.92   686.9 2449.88   696.8 2455.71
   706.8 2463.98   776.4  2489.1   786.4 2494.23   796.3 2496.89   826.2 2496.21
#Mann= 3 , 0 , 0
       0      .1       0   410.7    .045       0   425.7      .1       0
Bank Sta=410.7,425.7
XS Rating Curve= 0 ,0
Exp/Cntr=0.3,0.1

Type RM Length L Ch R = 1 ,38258.2 ,131.5,134.2,137
XS GIS Cut Line= 3
     1912532.062      171284.019     1912506.752       171174.99
      1912025.86        170947.2
#Sta/Elev= 30
       0 2413.58      28 2407.46    65.3    2401   102.6 2398.52   111.9 2395.58
   121.8 2397.09   141.5 2397.58     171 2396.67   180.9 2394.63   190.8 2390.46
     240 2362.91   269.6 2350.17   289.3 2335.35   299.2 2330.77   318.9 2324.34
   332.5 2322.49   338.6 2322.48   347.5 2324.35   387.8 2339.57   417.4 2346.09
   437.1 2349.32   456.8  2351.2   496.2 2351.07   535.6 2357.72   545.5 2360.54
   555.4 2365.37   584.9  2384.3   604.6 2394.79   624.3 2402.14     644 2405.97
#Mann= 3 , 0 , 0
       0      .1       0   332.5    .045       0   347.5      .1       0
Bank Sta=332.5,347.5
XS Rating Curve= 0 ,0
Exp/Cntr=0.3,0.1

Type RM Length L Ch R = 1 ,38124.2 ,169.9,204.6,238.6
XS GIS Cut Line= 3
     1912481.345      171117.107     1912424.284      170997.635
     1912122.929      170806.836
#Sta/Elev= 30
       0 2375.44     9.5 2376.05    47.3 2364.01    75.7 2353.55     104 2341.09
   122.9 2337.94   132.4 2333.05   142.3 2329.16   162.1 2325.54   183.9 2320.44
   191.8  2319.2   198.9 2319.41   201.8  2319.5   211.7 2322.53   221.6  2327.4
   231.5  2334.5   241.4 2338.83   300.8 2361.41   310.7 2367.19   320.6 2376.08
   330.6 2386.84   350.4 2400.68   370.2  2411.1   409.8 2429.12   419.7 2435.91
   429.6 2440.82   449.4 2447.45   459.4 2448.39   469.3 2451.14   489.1 2460.82
#Mann= 3 , 0 , 0
       0      .1       0   183.9    .045       0   198.9      .1       0
Bank Sta=183.9,198.9
XS Rating Curve= 0 ,0
Exp/Cntr=0.3,0.1

Type RM Length L Ch R = 1 ,37919.4 ,421.3,416.4,411.6
XS GIS Cut Line= 4
     1912528.168      171173.044     1912461.973      171011.448
     1912574.164      170768.644     1912259.492      170544.185
#Sta/Elev= 30
       0 2379.24    19.4 2374.41    58.2 2368.04    67.9 2369.23   164.9 2338.26
   273.7  2324.2   324.8 2312.92   333.1  2311.9   339.8 2312.48   352.9 2316.15
   372.8 2327.46   382.7 2328.46   392.6 2332.44   412.4 2349.04   442.1 2378.29
     452 2381.62   491.6 2386.85   511.5 2379.38   521.4 2379.48   531.3 2376.41
   541.2 2375.78   570.9 2377.96   620.5 2384.97   660.1 2382.16   689.9 2377.55
   709.7 2377.66   719.6 2380.26   729.5  2389.3   759.2 2405.56   828.6 2437.26
#Mann= 3 , 0 , 0
       0      .1       0   324.8    .045       0   339.8      .1       0
Bank Sta=324.8,339.8
XS Rating Curve= 0 ,0
Exp/Cntr=0.3,0.1

Type RM Length L Ch R = 1 ,37503   ,432,423.2,414.3
XS GIS Cut Line= 3
     1912707.286      171556.589     1912822.155      171050.387
     1912955.337      170678.796
#Sta/Elev= 30
       0  2490.5    49.9 2472.59    59.9 2471.95   139.8 2442.44   149.7 2442.01
   199.6 2425.83   239.6 2400.79   259.5 2394.78   269.5 2388.43   289.5 2372.08
   339.4 2324.53   359.4 2315.75   369.3 2309.55   396.4 2306.33   411.4 2305.07
   429.2 2303.91   499.1 2306.78   548.7 2313.15   568.4 2318.59     598 2333.31
   637.5 2360.63   657.2 2367.96   696.7 2396.12   736.2  2421.5     746 2425.62
   755.9 2427.17   834.9 2469.68   844.7 2473.52   864.5 2476.96   913.8 2497.99
#Mann= 3 , 0 , 0
       0      .1       0   396.4    .045       0   411.4      .1       0
Bank Sta=396.4,411.4
XS Rating Curve= 0 ,0
Exp/Cntr=0.3,0.1

Type RM Length L Ch R = 1 ,37079.7 ,334.2,337,339.7
XS GIS Cut Line= 2
     1913266.016      171464.371     1913134.698      170653.703
#Sta/Elev= 30
       0 2427.87    59.4 2418.16    79.2 2412.38   138.5 2381.34   148.4 2380.21
     188  2357.8   207.8 2348.56   237.5 2336.78   247.4 2336.56   257.2 2333.04
   306.7 2312.74     403 2295.71   415.6  2295.1     418 2295.47   445.2 2299.38
     465 2306.45   494.7 2320.99   534.3 2345.22   544.2 2346.73     564 2362.64
   603.6 2402.59   623.4 2417.48   633.2 2424.09   643.1 2424.54     653 2430.67
   692.6 2448.73   712.4  2454.7   732.2 2456.55   791.6 2453.24   821.2 2449.88
#Mann= 3 , 0 , 0
       0      .1       0     403    .045       0     418      .1       0
Bank Sta=403,418
XS Rating Curve= 0 ,0
Exp/Cntr=0.3,0.1