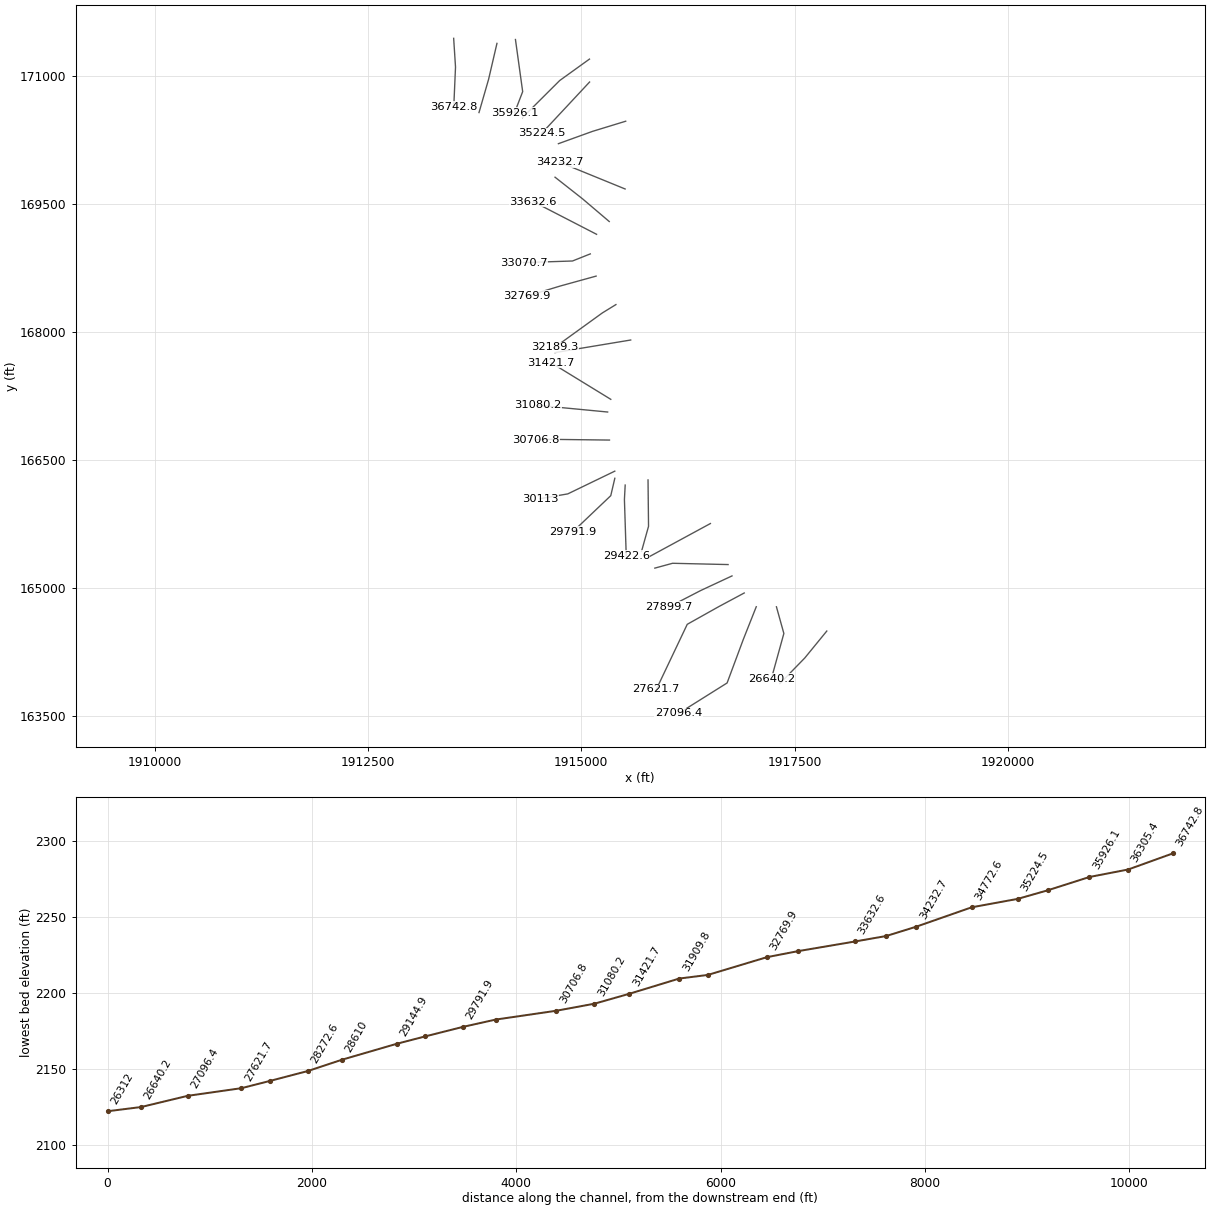
HEC-RAS study RchCrk.prj: RchCrk

--- RchCrk.g01 (geometry) --- (continued)

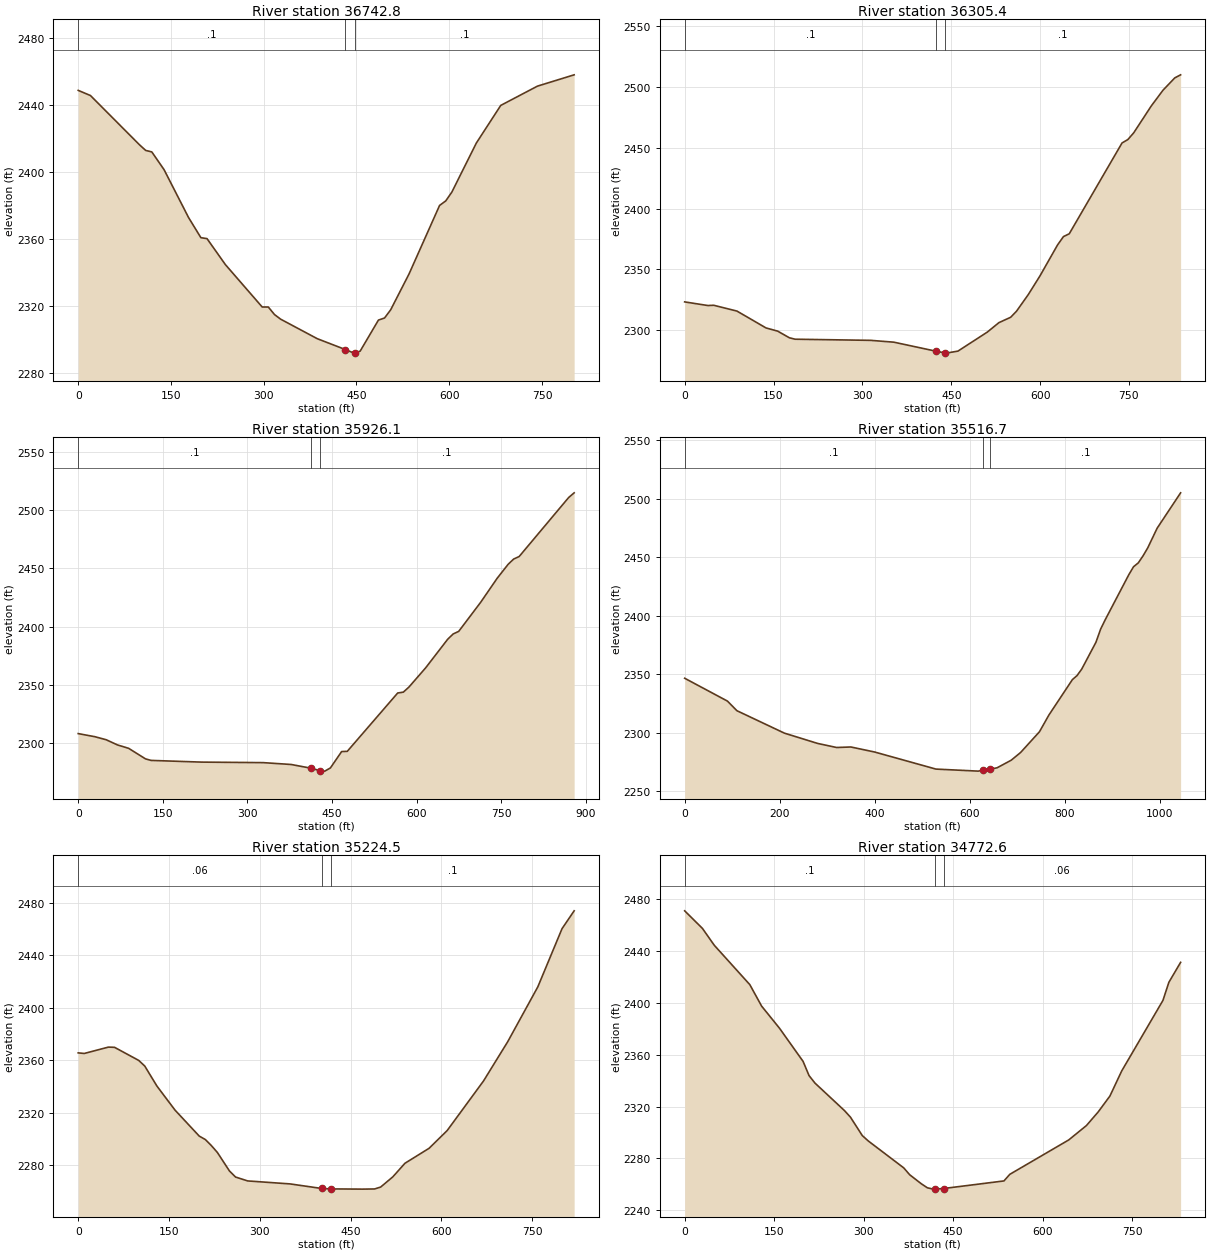
Type RM Length L Ch R = 1 ,36742.8 ,441.7,437.4,431.9
XS GIS Cut Line= 3
     1913503.829      171436.284     1913525.484       171099.79
     1913505.041      170635.447
#Sta/Elev= 30
       0 2448.91    19.8 2445.82    99.2  2416.3   109.1 2412.97     119 2412.07
   138.8 2401.47   178.5 2372.74   198.4 2360.72   208.3 2360.15     238  2344.6
   297.5 2319.22   307.4  2319.2   317.4 2314.71   327.3 2311.94   386.6 2300.24
   432.2 2293.72     446  2291.6   447.2 2291.74   455.9 2292.77   485.5 2311.38
   495.4 2312.63   505.3 2317.54     535 2339.01   584.4 2380.03   594.3 2382.72
   604.2 2387.98   643.8 2417.36   683.3 2439.91   742.6 2451.44     802 2458.22
#Mann= 3 , 0 , 0
       0      .1       0   432.2    .045       0   447.2      .1       0
Bank Sta=432.2,447.2
XS Rating Curve= 0 ,0
Exp/Cntr=0.3,0.1

Type RM Length L Ch R = 1 ,36305.4 ,371,379.3,388.8
XS GIS Cut Line= 3
     1914011.069      171377.156     1913913.204      170956.788
     1913800.634      170567.124
#Sta/Elev= 30
       0 2323.17    39.2 2320.18      49  2320.4    88.3 2315.61   137.3 2301.76
     157 2299.12   176.6 2293.69   186.4 2292.48   313.9 2291.54   353.1 2290.04
   424.1 2282.63   439.1 2281.19   441.5 2281.03   461.3 2282.69   510.8 2298.31
   530.5 2306.12   550.3 2310.52   560.2 2315.53     580 2329.16   599.8 2344.58
   629.5 2370.06   639.4 2376.88   649.2  2379.2   738.3 2453.91   748.2 2456.75
   758.1 2462.31   787.8 2484.46   807.5 2497.33   827.3 2507.43   837.2 2509.97
#Mann= 3 , 0 , 0
       0      .1       0   424.1    .045       0   439.1      .1       0
Bank Sta=424.1,439.1
XS Rating Curve= 0 ,0
Exp/Cntr=0.3,0.1

Type RM Length L Ch R = 1 ,35926.1 ,430.4,409.3,388.2
XS GIS Cut Line= 3
     1914227.839      171422.494     1914312.531      170812.131
     1914217.962      170566.573
#Sta/Elev= 30
       0 2308.29    29.8  2305.6    49.7    2303    69.6 2298.57    89.4 2295.67
   119.3 2286.62   129.2  2285.3   218.7 2283.84     328 2283.39   377.7  2281.8
   413.5 2278.54   428.5 2276.54   437.3 2276.11   447.2 2278.85   467.1 2292.89
   477.1 2293.07   566.5 2343.09   576.5 2343.83   586.4 2348.15   616.2 2364.73
   655.2  2389.2   664.9  2393.7   674.7 2395.92   713.7 2420.89   742.9 2441.44
   762.4 2453.45   772.1  2457.9   781.9  2460.1   869.6 2510.64   879.4  2514.7
#Mann= 3 , 0 , 0
       0      .1       0   413.5    .045       0   428.5      .1       0
Bank Sta=413.5,428.5
XS Rating Curve= 0 ,0
Exp/Cntr=0.3,0.1

Type RM Length L Ch R = 1 ,35516.7 ,291.3,292.1,292.7
XS GIS Cut Line= 3
     1915095.197      171193.243     1914746.209      170942.089
     1914310.845      170508.614
#Sta/Elev= 30
       0 2346.62      90 2327.13     110 2318.92     210 2299.77     280 2290.98
     320 2287.52     350 2287.95     400 2283.66   529.1 2269.09   618.2 2267.35
   628.1 2268.18   643.1 2268.97   657.9 2270.21   687.6 2276.67   707.4 2283.27
   747.1 2300.96   766.9 2315.19   816.4 2345.44   826.3 2348.94   836.2 2354.52
     866 2377.32   875.9 2388.58   885.8 2396.76   935.3 2435.05   945.2  2441.8
   955.2 2445.08   965.1 2451.02     975 2457.82   994.8 2474.62  1044.3 2504.87
#Mann= 3 , 0 , 0
       0      .1       0   628.1    .045       0   643.1      .1       0
Bank Sta=628.1,643.1
XS Rating Curve= 0 ,0
Exp/Cntr=0.3,0.1

Type RM Length L Ch R = 1 ,35224.5 ,462,451.7,441.5
XS GIS Cut Line= 3
     1915096.375      170924.657     1914816.645      170625.004
     1914536.991      170325.968
#Sta/Elev= 30
       0 2365.59      10 2365.15      50    2370      60 2369.83     100 2359.85
     110 2355.53     130 2340.34     160 2321.95     200 2302.16     210 2299.57
     220 2294.95     230 2289.66     250 2275.53     260 2270.97     280 2268.01
   349.9 2265.74   402.5 2262.25   417.5 2261.93   469.8 2261.76   489.8 2261.89
   499.8 2263.37   519.8 2271.11   539.8 2281.45   579.7 2292.87   609.6 2306.39
   669.6 2344.15   709.5 2373.99   759.4 2415.92   799.4 2460.27   819.4 2473.85
#Mann= 3 , 0 , 0
       0     .06       0   402.5    .045       0   417.5      .1       0
Bank Sta=402.5,417.5
XS Rating Curve= 0 ,0
Exp/Cntr=0.3,0.1

Type RM Length L Ch R = 1 ,34772.6 ,556.5,540,523.5
XS GIS Cut Line= 3
     1915519.618      170465.759     1915130.518      170346.842
      1914731.32        170202.7
#Sta/Elev= 30
       0 2471.12    29.8 2457.53    49.6 2444.53   109.2 2414.12     129 2397.53
   158.8 2380.55   198.5 2354.84   208.4 2343.94   218.3 2338.14   267.9 2316.84
   277.9 2311.77   297.7 2297.58   307.6 2293.46   367.2 2272.62   377.1 2267.34
   396.9 2260.25   406.9 2257.22   416.7 2256.21   419.1 2256.24   434.1 2256.69
   535.2 2262.54     545 2267.64   643.8 2294.21   673.4 2305.29   693.1  2315.8
   712.8  2328.1   732.6 2347.51   801.7 2401.96   811.6 2415.92   831.3 2431.33
#Mann= 3 , 0 , 0
       0      .1       0   419.1    .045       0   434.1     .06       0
Bank Sta=419.1,434.1
XS Rating Curve= 0 ,0
Exp/Cntr=0.3,0.1

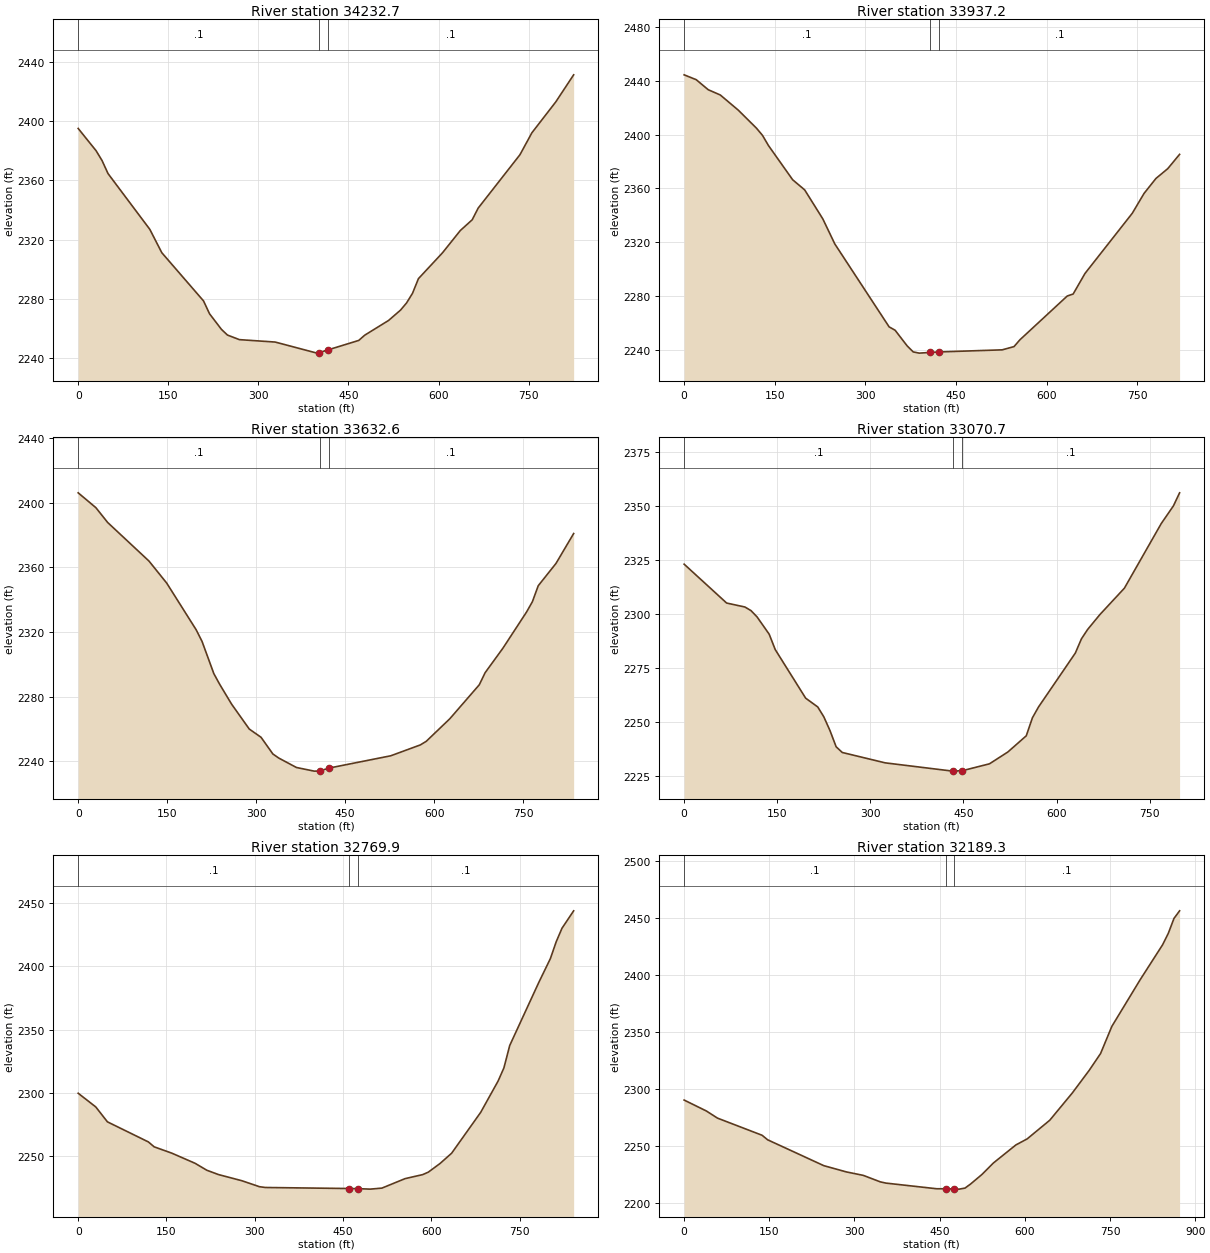
Type RM Length L Ch R = 1 ,34232.7 ,302.3,295.4,289.1
XS GIS Cut Line= 2
     1915512.938      169672.385     1914749.143      169984.045
#Sta/Elev= 30
       0 2394.97    29.8 2379.96    39.8 2373.28    49.7 2364.53   119.3 2326.95
   139.2 2311.23   208.7 2278.72   218.7 2270.06   238.5 2259.56   248.5 2255.72
   268.4 2252.63     328    2251   397.6 2243.54   401.6 2243.96   416.6 2245.81
   467.1  2252.1   477.1 2255.64   516.8 2265.57   536.7 2272.54   546.6  2277.3
   556.6 2283.84   566.5 2293.74   606.3 2311.04   636.1 2326.12     656 2333.41
   665.9 2341.25   735.5 2377.26   755.4 2392.06   795.1 2412.84   824.9 2431.11
#Mann= 3 , 0 , 0
       0      .1       0   401.6    .045       0   416.6      .1       0
Bank Sta=401.6,416.6
XS Rating Curve= 0 ,0
Exp/Cntr=0.3,0.1

Type RM Length L Ch R = 1 ,33937.2 ,299.6,304.6,309
XS GIS Cut Line= 3
     1915326.912      169291.247     1915015.047      169556.217
     1914691.845      169810.159
#Sta/Elev= 30
       0 2444.64      20 2441.03    39.9 2433.55    59.9 2429.62    89.8 2418.28
   119.8 2404.89   129.8 2399.52   139.7 2391.93   179.7 2366.49   199.6 2358.94
   229.6 2337.37   249.5 2318.68   339.4 2256.93   349.3 2254.43   369.3 2242.76
   379.3 2238.28   389.3 2237.38   407.6 2237.88   422.6 2238.27   526.7 2239.83
   546.2 2242.25     556 2247.33   634.3 2279.91   644.1 2281.41   663.7 2296.73
     742 2341.56   761.5 2356.34   781.1 2367.44   800.7 2374.76   820.3 2385.41
#Mann= 3 , 0 , 0
       0      .1       0   407.6    .045       0   422.6      .1       0
Bank Sta=407.6,422.6
XS Rating Curve= 0 ,0
Exp/Cntr=0.3,0.1

Type RM Length L Ch R = 1 ,33632.6 ,550.4,561.9,573.3
XS GIS Cut Line= 2
     1915178.428      169141.664      1914435.93      169524.327
#Sta/Elev= 30
       0 2406.26    29.8 2397.07    49.7 2387.88   119.3    2364   149.2 2350.34
   198.9  2321.4   208.8  2314.2   228.7 2294.21   238.7 2287.51   258.6 2275.33
   288.4 2259.89   308.3 2254.76   328.2 2244.44   338.1 2241.91   367.9 2236.06
   397.8  2233.8   407.1 2233.85   422.1 2235.63     527 2243.31   576.8 2250.04
   586.7 2252.24   626.5 2266.24   676.2  2287.3   686.1 2294.82     716 2309.95
   755.8 2332.34   765.7 2338.75   775.6 2348.68   805.5 2362.49   835.3 2381.03
#Mann= 3 , 0 , 0
       0      .1       0   407.1    .045       0   422.1      .1       0
Bank Sta=407.1,422.1
XS Rating Curve= 0 ,0
Exp/Cntr=0.3,0.1

Type RM Length L Ch R = 1 ,33070.7 ,294.1,300.6,307.4
XS GIS Cut Line= 3
     1915105.053      168912.231      1914895.88      168828.999
     1914323.117      168810.382
#Sta/Elev= 30
       0 2323.21    68.5 2305.21    97.9 2303.38   107.7 2301.72   117.5 2298.79
     137 2290.81   146.8 2283.66   195.8 2261.18   215.3 2257.11   225.1 2252.52
     235 2246.16   244.9 2238.68   254.8 2236.04   323.9 2231.24   432.6 2227.41
   433.3 2227.41   448.3 2227.62   491.9 2230.79   521.5 2236.26   551.2 2243.76
   561.1 2252.09   570.9 2257.09   630.2 2282.04   640.1 2288.65     650 2292.96
   669.7 2299.84   709.3  2312.1   768.6 2341.98   788.3 2350.21   798.2 2356.23
#Mann= 3 , 0 , 0
       0      .1       0   433.3    .045       0   448.3      .1       0
Bank Sta=433.3,448.3
XS Rating Curve= 0 ,0
Exp/Cntr=0.3,0.1

Type RM Length L Ch R = 1 ,32769.9 ,573.4,580.2,586.9
XS GIS Cut Line= 3
     1915173.074      168652.147     1914751.795      168535.832
     1914364.598      168418.377
#Sta/Elev= 30
       0 2299.49    29.8 2288.67    49.7 2276.82   119.2 2260.93   129.1 2257.02
   158.9 2252.04   198.7 2243.96   218.5 2238.48   238.4 2235.04   278.1 2230.16
   307.9 2225.44   317.8 2224.81   459.8 2223.99   474.8 2223.88   496.2 2223.51
     516 2224.32   555.5 2231.85   585.1 2234.99   594.9 2236.99   614.7 2243.81
   634.4 2251.96   683.8 2284.36   713.4 2309.19   723.2 2319.55   733.1 2337.32
   782.4  2387.2   802.2 2406.22   812.1 2419.57   821.9 2430.24   841.7 2444.04
#Mann= 3 , 0 , 0
       0      .1       0   459.8    .045       0   474.8      .1       0
Bank Sta=459.8,474.8
XS Rating Curve= 0 ,0
Exp/Cntr=0.3,0.1

Type RM Length L Ch R = 1 ,32189.3 ,289.8,279.5,269.1
XS GIS Cut Line= 3
     1915405.124       168318.66     1915246.327      168221.192
     1914689.992      167819.272
#Sta/Elev= 30
       0 2289.97    39.2 2280.36    58.8  2274.1   137.3 2259.08   147.1 2255.09
     246 2232.41   285.8 2226.91   315.6 2223.88   345.5 2218.19   355.4 2217.11
   444.9 2212.14     461 2212.14     476 2211.88   484.7 2211.82   494.7 2212.74
   504.6 2216.33   524.5 2224.68   544.4 2234.63   584.2 2250.56   604.1 2255.88
   643.9 2272.23   683.7  2296.2   713.5  2316.1   733.4 2330.74   753.3 2354.62
     803  2395.4   842.8 2426.29   852.8 2436.31   862.7 2449.29   872.6 2455.98
#Mann= 3 , 0 , 0
       0      .1       0     461    .045       0     476      .1       0
Bank Sta=461,476
XS Rating Curve= 0 ,0
Exp/Cntr=0.3,0.1

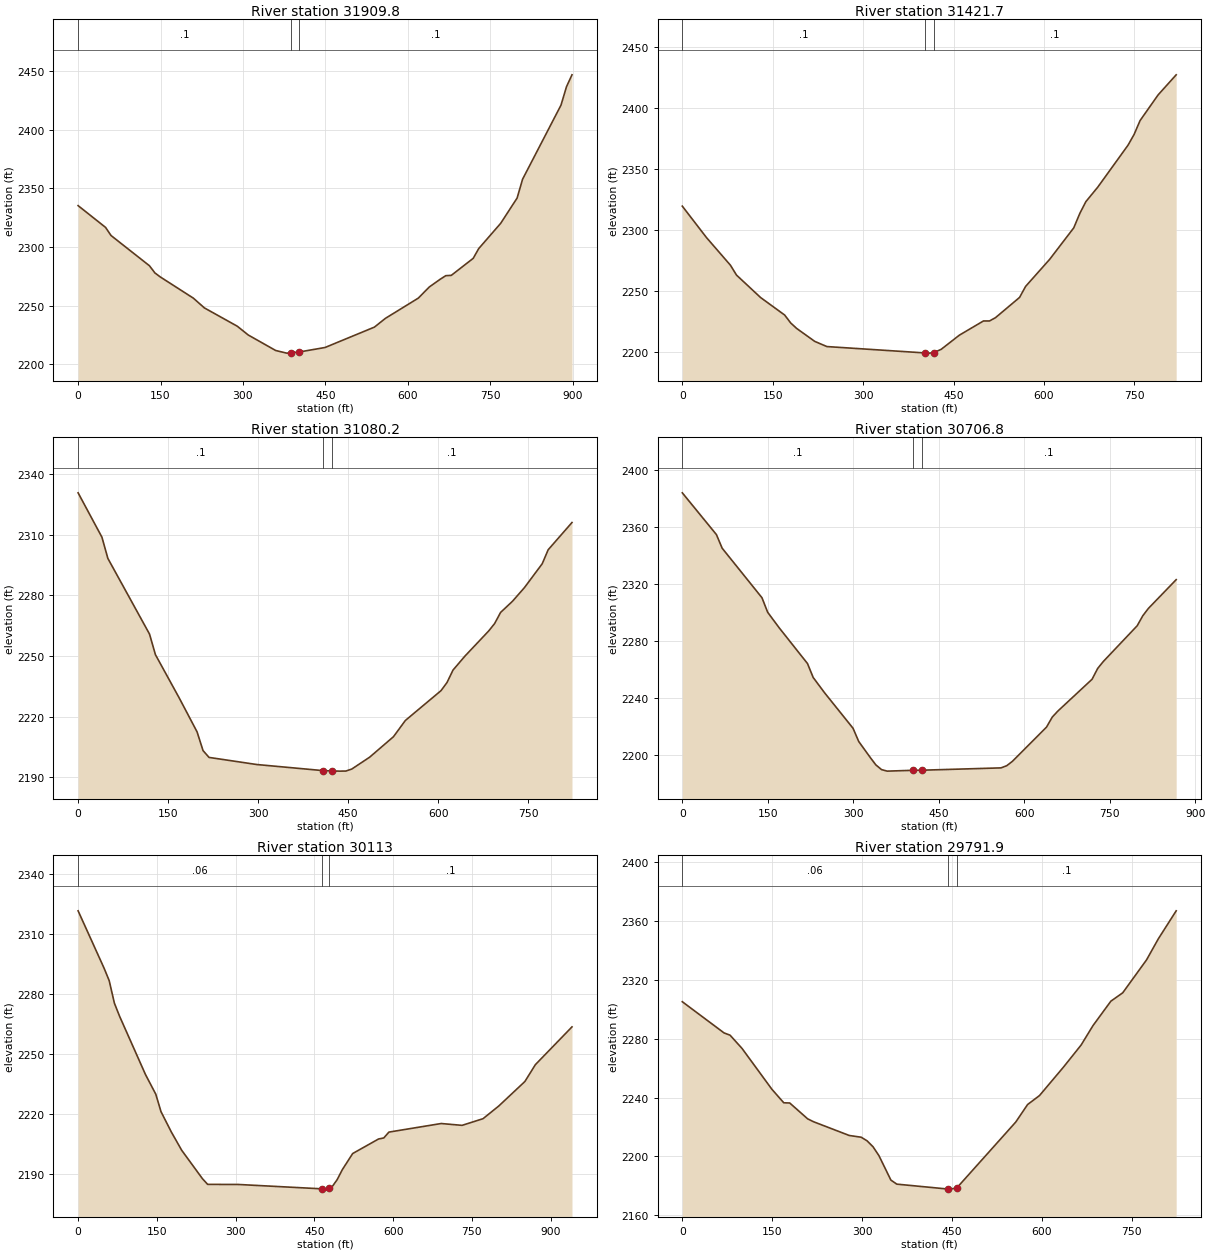
Type RM Length L Ch R = 1 ,31909.8 ,504.3,488.2,472.1
XS GIS Cut Line= 2
     1915578.315      167903.841     1914691.446      167756.529
#Sta/Elev= 30
       0 2335.17      50 2316.62    59.9 2309.73   129.9 2283.91   139.8 2277.82
   149.8 2274.33   209.8 2256.31   229.8 2248.03   289.7 2232.41   309.7 2224.91
   359.6 2211.71   379.6 2209.46   386.7 2209.74   401.7 2210.36   449.5 2214.26
   539.4 2231.64   559.4 2239.09   619.3 2256.35   639.3 2265.86   659.3 2272.48
   669.3 2275.48   679.3 2275.74   719.2 2290.25   729.2 2298.54   769.2 2320.09
   799.1 2341.62   809.1 2357.72     879 2420.84     889  2436.5     899 2446.67
#Mann= 3 , 0 , 0
       0      .1       0   386.7    .045       0   401.7      .1       0
Bank Sta=386.7,401.7
XS Rating Curve= 0 ,0
Exp/Cntr=0.3,0.1

Type RM Length L Ch R = 1 ,31421.7 ,331.2,341.5,351.7
XS GIS Cut Line= 2
      1915344.85      167209.352     1914646.269      167637.405
#Sta/Elev= 30
       0 2319.69      40 2294.05    79.9 2271.34    89.9 2263.31   129.9 2244.93
   169.8 2230.62   179.8 2224.15   189.8 2219.62   219.8 2209.05   239.8 2204.84
   402.4 2199.63   409.6 2199.47   417.4 2199.88   429.6 2202.63   459.6 2214.15
   499.6 2225.78   509.6 2225.78   519.6 2228.48   559.5 2245.03   569.5 2254.03
   609.5 2276.22   649.4 2301.94   659.4 2313.69   669.4 2323.31   689.4 2335.35
   739.4 2369.53   749.4 2378.25   759.4 2389.67   789.3 2410.66   819.3 2427.09
#Mann= 3 , 0 , 0
       0      .1       0   402.4    .045       0   417.4      .1       0
Bank Sta=402.4,417.4
XS Rating Curve= 0 ,0
Exp/Cntr=0.3,0.1

Type RM Length L Ch R = 1 ,31080.2 ,371.5,373.4,375.3
XS GIS Cut Line= 2
     1915308.139      167060.646     1914488.793      167139.131
#Sta/Elev= 30
       0 2330.76    39.7  2308.8    49.6 2298.28     119 2260.83   128.9  2250.6
   168.6 2229.13   198.3 2212.37   208.2 2203.13   218.2 2199.74   297.5 2196.23
   408.2  2193.2   423.2 2193.03   436.3 2192.95   446.3 2192.99   456.2 2193.99
   485.9 2199.86   525.6 2209.99   545.4 2218.03   604.9 2232.82   614.8 2236.82
   624.8 2242.98   644.6 2249.87   684.3 2262.36   694.2 2266.04   704.1 2271.53
   723.9 2277.05   743.8  2283.8   773.5 2295.64   783.4 2302.56   823.1 2316.06
#Mann= 3 , 0 , 0
       0      .1       0   408.2    .045       0   423.2      .1       0
Bank Sta=408.2,423.2
XS Rating Curve= 0 ,0
Exp/Cntr=0.3,0.1

Type RM Length L Ch R = 1 ,30706.8 ,582.9,593.3,603.8
XS GIS Cut Line= 3
     1915329.708      166732.333     1914560.764      166741.646
     1914463.296      166735.075
#Sta/Elev= 30
       0 2384.17    59.9 2354.76    69.9 2345.23   139.8 2310.34   149.8 2300.12
   169.8 2289.29   219.7 2264.02   229.7 2254.21   249.7 2243.44   299.6  2218.5
   309.6 2209.17   329.6 2198.05   339.6 2192.73   349.6  2189.4   359.5 2188.32
   404.9 2188.89   419.9 2188.96   559.3  2190.6   569.3 2192.13   579.2 2195.18
   639.2 2219.31   649.2 2226.33   659.1  2230.6   719.1 2252.97     729 2260.61
     739 2265.54   798.3 2290.64   808.1 2297.65   817.8 2302.76   866.7 2323.06
#Mann= 3 , 0 , 0
       0      .1       0   404.9    .045       0   419.9      .1       0
Bank Sta=404.9,419.9
XS Rating Curve= 0 ,0
Exp/Cntr=0.3,0.1

Type RM Length L Ch R = 1 ,30113   ,314.2,321.2,328.2
XS GIS Cut Line= 3
     1915391.982        166368.2     1914841.122      166102.079
     1914516.958      166046.226
#Sta/Elev= 30
       0 2321.68    49.3  2293.1    59.2 2286.78    69.1 2275.52    78.9 2269.03
   128.3 2239.85     148 2229.97   157.9 2221.26   177.6 2211.08   197.4 2201.92
   236.8 2187.76   246.7 2184.91   305.9 2184.85   463.8 2182.68   473.6 2182.53
   478.8  2183.1   483.5 2183.61   493.4 2187.25   503.2 2192.24     523 2200.33
   572.3  2207.6   582.2 2208.12     592 2211.04   691.5 2215.33   731.4 2214.42
   771.3 2217.75   801.2 2224.08     851 2236.34   870.9 2244.74   940.7 2263.65
#Mann= 3 , 0 , 0
       0     .06       0   463.8    .045       0   478.8      .1       0
Bank Sta=463.8,478.8
XS Rating Curve= 0 ,0
Exp/Cntr=0.3,0.1

Type RM Length L Ch R = 1 ,29791.9 ,350.2,369.3,388.3
XS GIS Cut Line= 3
      1915392.34      166284.936     1915344.891      166081.271
     1914899.165      165657.631
#Sta/Elev= 30
       0 2305.19    69.7 2283.96    79.7 2282.43    99.6 2273.45   149.4 2245.69
   169.3 2236.45   179.2 2236.32   209.1 2225.55     219 2223.56   278.6 2214.21
   298.4 2213.04   308.3 2210.57   318.2 2206.55   328.1 2200.48     348 2183.89
   357.9 2181.12     443 2177.79   447.2 2177.73     458 2178.56   556.3 2223.33
   576.1 2235.27   595.9 2241.35   635.6 2260.54   665.4 2275.75   685.2 2288.95
     715 2305.56   734.8 2311.25   774.5 2333.62   794.3 2348.03     824 2367.02
#Mann= 3 , 0 , 0
       0     .06       0     443    .045       0     458      .1       0
Bank Sta=443,458
XS Rating Curve= 0 ,0
Exp/Cntr=0.3,0.1

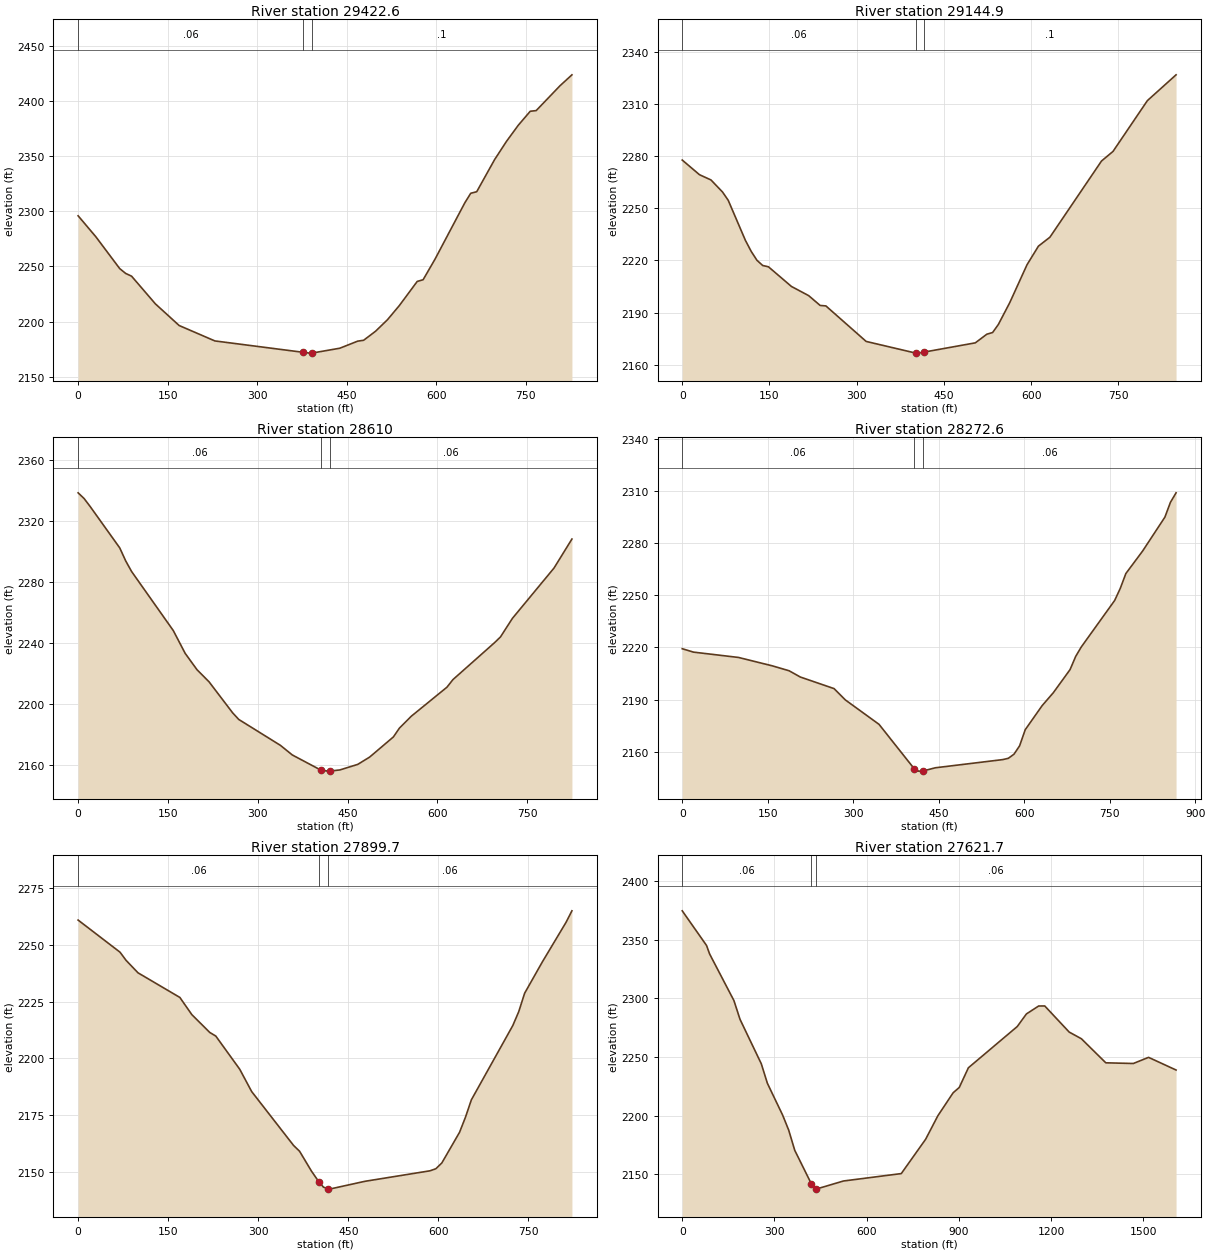
Type RM Length L Ch R = 1 ,29422.6 ,278.3,277.7,277.1
XS GIS Cut Line= 3
     1915513.744      166205.414     1915504.782       166036.37
     1915526.041      165378.733
#Sta/Elev= 30
       0 2295.85    29.9 2276.74    69.7 2248.03    79.7 2243.65    89.6 2241.16
   129.4 2216.13   169.3 2196.48   229.1 2182.53   376.7 2172.24   388.6 2171.48
   391.7 2171.51   438.5 2175.93   468.4 2182.33   478.3 2183.11   498.3 2191.28
   518.2 2201.68   538.2 2214.56   568.1 2236.39     578 2237.94     598 2256.63
   647.8 2307.53   657.8 2316.24   667.8 2317.64   697.7 2346.67   717.6 2363.19
   737.5 2377.88   757.5  2390.5   767.4  2391.1   807.3 2413.58   827.3 2423.49
#Mann= 3 , 0 , 0
       0     .06       0   376.7    .045       0   391.7      .1       0
Bank Sta=376.7,391.7
XS Rating Curve= 0 ,0
Exp/Cntr=0.3,0.1

Type RM Length L Ch R = 1 ,29144.9 ,559.5,534.8,510.2
XS GIS Cut Line= 3
     1915781.465      166265.461     1915787.331      165722.062
      1915704.92      165427.848
#Sta/Elev= 30
       0  2277.8    29.6 2269.38    49.4 2266.35    69.2 2259.42      79 2254.67
   108.7 2231.49   118.6  2225.2   128.4 2220.12   138.3 2217.11   148.2 2216.35
   187.7 2205.04   217.4 2199.74   237.1  2194.1     247 2193.82   316.2 2173.38
   401.3 2166.68   405.1 2166.65   416.3 2167.28   503.9 2172.57   523.7 2177.55
   533.6 2178.51   543.4  2183.1   563.1 2195.73   592.7  2217.5   612.4 2228.25
   632.1 2233.38   720.8 2277.24   740.6 2282.78   799.7 2312.02     849 2326.87
#Mann= 3 , 0 , 0
       0     .06       0   401.3    .045       0   416.3      .1       0
Bank Sta=401.3,416.3
XS Rating Curve= 0 ,0
Exp/Cntr=0.3,0.1

Type RM Length L Ch R = 1 ,28610   ,349.1,337.4,325.6
XS GIS Cut Line= 2
     1916512.319      165754.917     1915787.243      165362.073
#Sta/Elev= 30
       0 2338.78     9.9 2335.09    19.9 2329.93    69.6 2302.62    79.5 2294.12
    89.4 2287.13     159  2248.4   178.8 2233.48   198.7 2222.68   218.6 2214.85
   258.3 2194.36   268.3 2190.12   337.8 2173.15   357.7 2166.83   405.2 2156.93
   417.3 2156.22   420.2 2156.26   437.2    2157     467 2160.64   486.8  2165.4
   526.6 2178.67   536.5 2184.38   556.4 2192.22     616 2211.28     626 2216.26
   695.5 2240.49   705.4 2244.26   725.3 2256.42   794.8 2289.44   824.7 2308.46
#Mann= 3 , 0 , 0
       0     .06       0   405.2    .045       0   420.2     .06       0
Bank Sta=405.2,420.2
XS Rating Curve= 0 ,0
Exp/Cntr=0.3,0.1

Type RM Length L Ch R = 1 ,28272.6 ,361.4,372.3,384.2
XS GIS Cut Line= 3
      1916719.78      165274.438     1916068.784      165289.479
      1915861.06      165232.828
#Sta/Elev= 30
       0 2219.26    19.7  2217.3    98.7 2214.23   157.9 2209.41   187.5 2206.56
   207.2 2202.95   266.4 2196.28   286.1 2189.79   345.3 2175.69   406.8 2150.22
   414.4 2148.74   421.8 2148.77     444 2150.66   562.4 2155.38   572.2 2156.13
   582.1 2158.49     592 2163.35   601.8 2172.58   631.4 2186.42   651.2 2193.95
   680.5 2207.23   690.3 2214.78   700.1 2220.23   758.8 2247.08   768.6 2254.03
   778.4 2262.57   807.8 2275.53   846.9 2295.06   856.7 2303.65   866.5 2309.07
#Mann= 3 , 0 , 0
       0     .06       0   406.8    .045       0   421.8     .06       0
Bank Sta=406.8,421.8
XS Rating Curve= 0 ,0
Exp/Cntr=0.3,0.1

Type RM Length L Ch R = 1 ,27899.7 ,276.8,277.9,278
XS GIS Cut Line= 3
     1916765.484      165141.599     1916395.072      164968.768
     1916027.585      164778.644
#Sta/Elev= 30
       0 2261.03    69.8 2246.85    79.8 2243.27    99.7 2237.75   169.5 2226.86
   189.4 2219.28   219.3  2211.4   229.3 2209.82   269.2 2195.16   289.1  2185.3
   358.9  2161.5   368.9 2158.94   388.8 2150.13   401.2 2145.36   408.8 2143.06
   416.2 2142.43   418.6 2142.22   477.7 2145.67   586.1 2150.31   595.9 2151.23
   605.8 2153.77   635.3  2167.3   645.2 2173.99     655 2181.65     724 2214.44
   733.8  2220.5   743.7 2228.71   773.2 2242.54   812.6 2259.98   822.5 2265.11
#Mann= 3 , 0 , 0
       0     .06       0   401.2    .045       0   416.2     .06       0
Bank Sta=401.2,416.2
XS Rating Curve= 0 ,0
Exp/Cntr=0.3,0.1

Type RM Length L Ch R = 1 ,27621.7 ,508.3,524.7,541.5
XS GIS Cut Line= 4
     1916908.764      164941.706     1916612.343      164782.972
     1916241.043      164574.895     1915878.399      163812.544
#Sta/Elev= 30
       0  2374.5    79.1 2344.97      89 2337.78   168.1 2298.06   187.9  2282.1
   257.1 2244.24   276.9 2227.64   326.4 2200.59   346.2 2187.77   365.9 2170.55
   419.5  2142.2   434.5 2137.59   435.2 2137.48   524.3  2144.4   712.4 2150.72
   791.7 2179.99   831.4 2199.98   881.1 2219.55   900.9 2224.04   930.7 2240.84
  1089.6 2275.96  1119.4 2286.69  1159.2 2293.44    1179 2293.48  1258.5 2271.24
  1298.2 2265.54  1377.6 2245.06    1467 2244.47  1516.7  2249.7  1606.1 2238.92
#Mann= 3 , 0 , 0
       0     .06       0   419.5    .045       0   434.5     .06       0
Bank Sta=419.5,434.5
XS Rating Curve= 0 ,0
Exp/Cntr=0.3,0.1

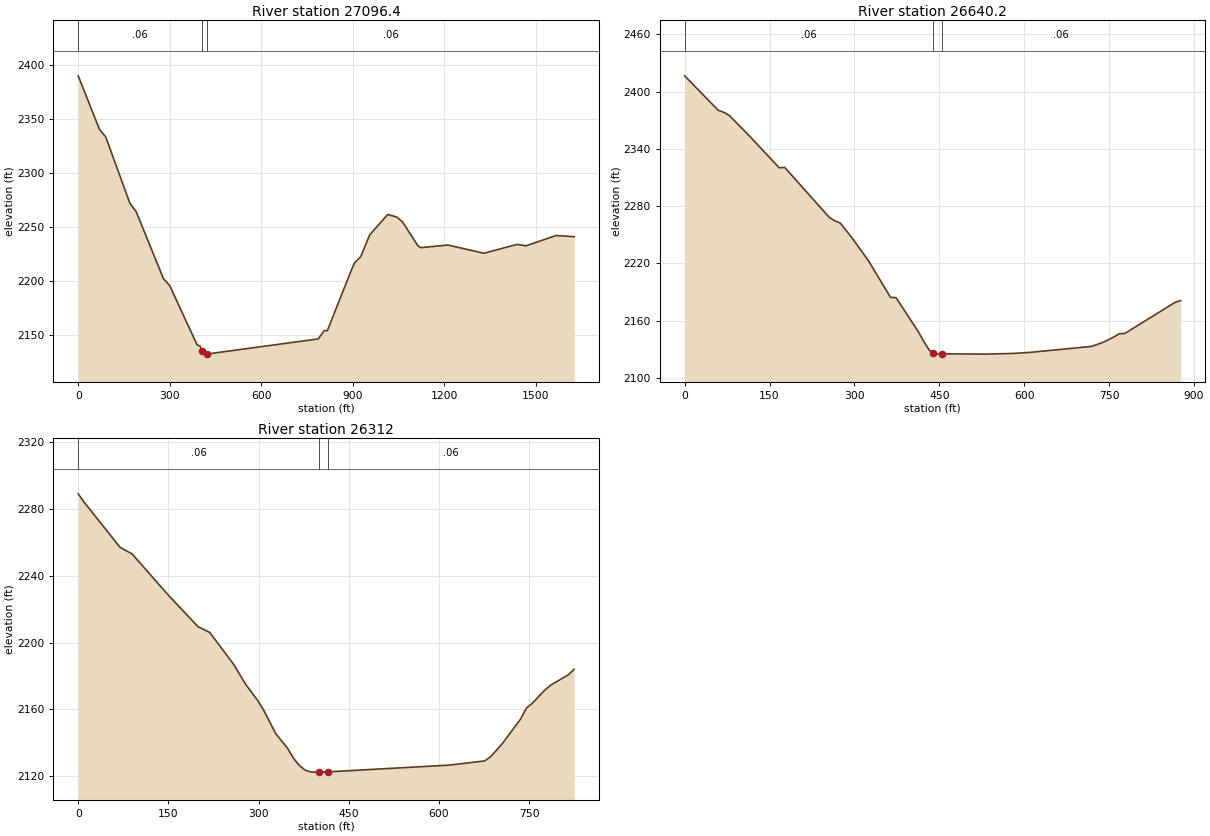
Type RM Length L Ch R = 1 ,27096.4 ,453.7,456.1,458.2
XS GIS Cut Line= 4
     1917049.797      164780.866     1916898.691      164400.042
     1916708.005      163888.079     1916139.929      163531.993
#Sta/Elev= 30
       0 2389.57      70 2339.99    89.9 2333.34   169.9 2271.61   189.9  2264.2
   279.8 2202.07   299.8 2195.96   389.7  2141.2   399.7 2139.84   406.1 2135.76
   419.6 2132.48   421.1 2132.52   787.2 2146.53     807 2154.29     817 2154.04
   896.4 2210.53   906.4 2216.87   926.2 2222.37     956 2242.65  1015.2  2261.5
  1044.8 2259.12  1064.5  2254.3  1113.8 2232.64  1123.6 2230.83  1212.4 2233.27
  1330.7 2225.65  1439.2 2233.86  1468.7 2232.55  1567.3 2242.07  1626.5 2240.98
#Mann= 3 , 0 , 0
       0     .06       0   406.1    .045       0   421.1     .06       0
Bank Sta=406.1,421.1
XS Rating Curve= 0 ,0
Exp/Cntr=0.3,0.1

Type RM Length L Ch R = 1 ,26640.2 ,337.6,328.2,316.8
XS GIS Cut Line= 3
     1917286.107       164780.06     1917373.106       164467.57
      1917225.97      163935.301
#Sta/Elev= 30
       0 2416.47      59 2380.54    68.8 2378.37    78.6  2375.2     118  2351.3
   167.1 2320.19   176.9 2320.56   255.6 2268.27   265.4 2264.71   275.2 2262.26
   294.9 2247.52   324.4  2223.3   363.8 2184.58   373.7  2184.2   413.1 2148.46
     423 2138.02   432.8 2128.92   439.1 2126.75   442.7 2125.51   454.1 2125.42
   531.5 2125.12   580.8 2125.85   610.4 2126.95   718.8 2133.17   738.6 2137.25
   758.3 2142.95   768.1 2146.52     778 2146.75   866.7 2179.28   876.6 2181.16
#Mann= 3 , 0 , 0
       0     .06       0   439.1    .045       0   454.1     .06       0
Bank Sta=439.1,454.1
XS Rating Curve= 0 ,0
Exp/Cntr=0.3,0.1

Type RM Length L Ch R = 1 ,26312   ,494.5,509.4,526.2
XS GIS Cut Line= 3
     1917876.152      164495.906     1917617.669      164179.985
     1917326.552      163881.533
#Sta/Elev= 30
       0 2289.11      10 2284.04    69.7 2257.02    89.6 2253.13   149.3 2228.66
   199.1 2209.58     219 2206.01   258.8  2186.8   278.8 2174.86   298.7 2165.26
   308.6 2159.49   328.5 2145.51   348.5 2136.54   358.4 2130.55   368.4 2126.21
   378.3  2123.4   388.3 2122.36   400.7 2122.46   415.7 2122.53   616.6 2126.54
   676.2 2129.06   686.1 2131.57     706 2139.62   735.8 2154.05   745.7 2160.75
   755.6 2163.66   775.5 2171.26   785.4 2174.34   815.2 2180.64   825.1    2184
#Mann= 3 , 0 , 0
       0     .06       0   400.7    .045       0   415.7     .06       0
Bank Sta=400.7,415.7
XS Rating Curve= 0 ,0
Exp/Cntr=0.3,0.1