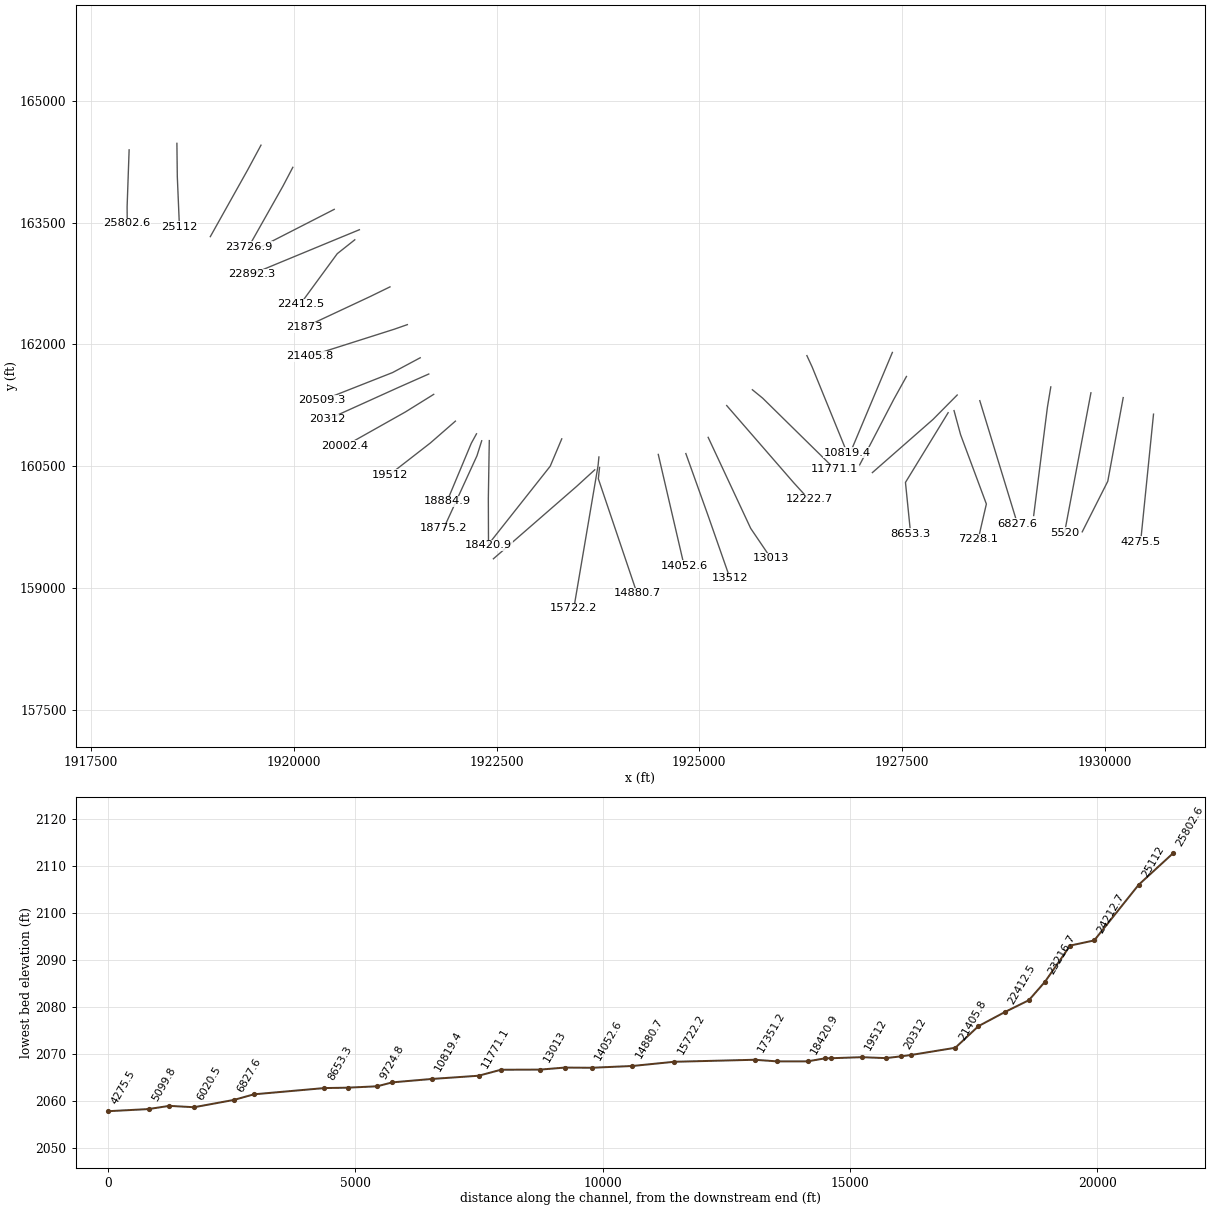
HEC-RAS study RchCrk.prj: RchCrk

--- RchCrk.g01 (geometry) --- (continued)

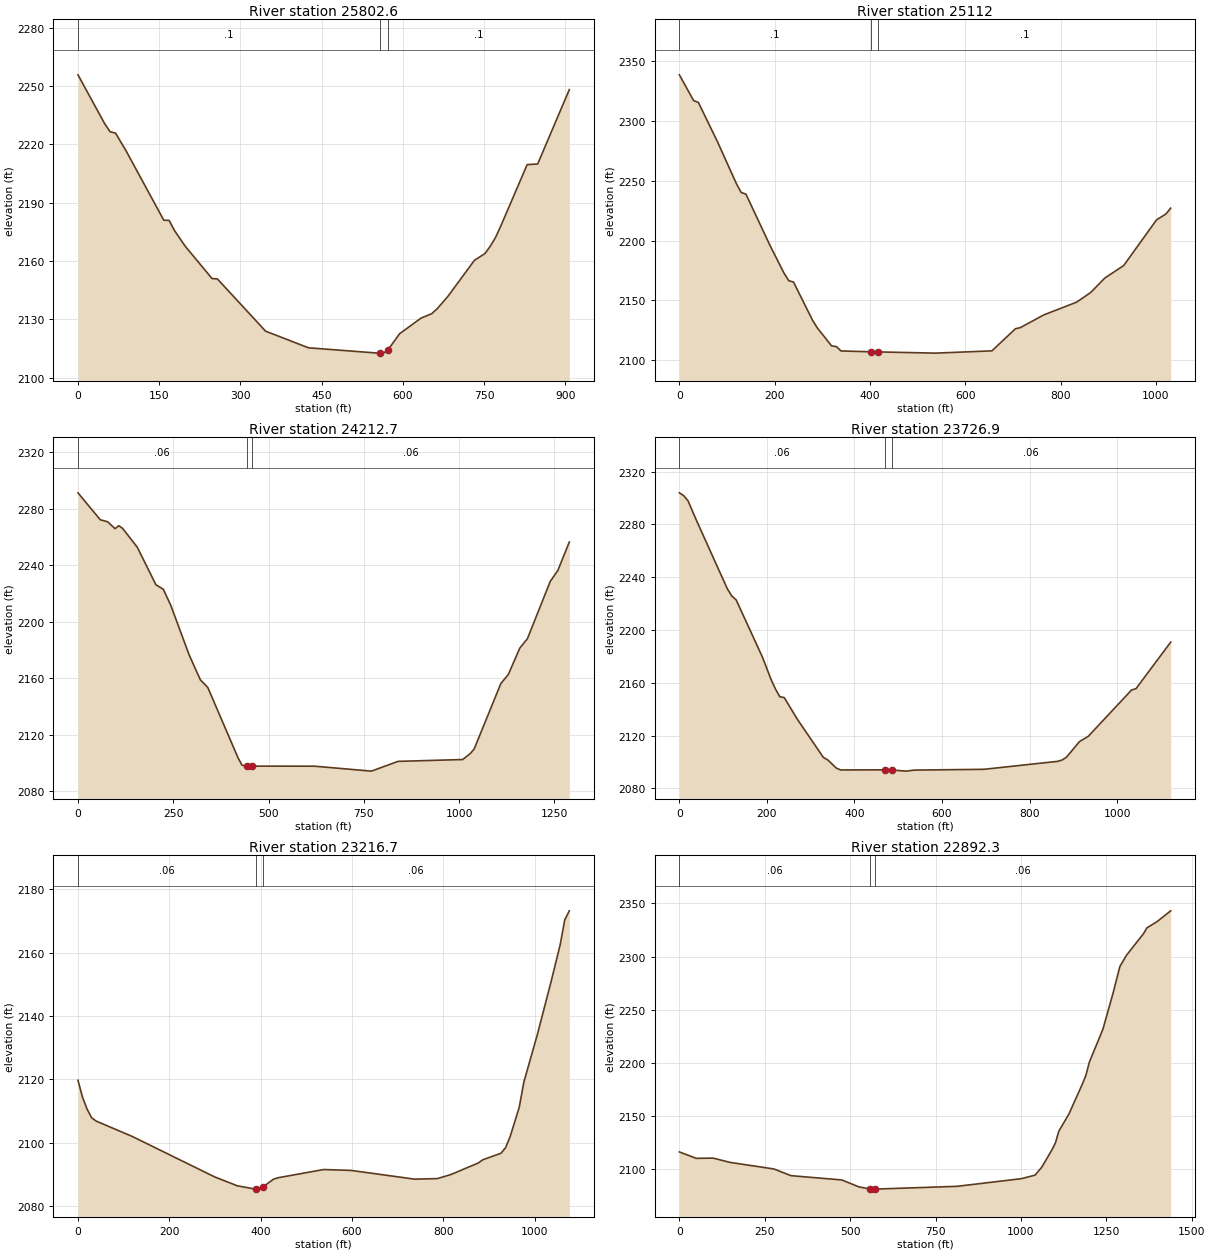
Type RM Length L Ch R = 1 ,25802.6 ,689.3,690.6,692.5
XS GIS Cut Line= 3
     1917968.867       164397.48     1917944.044      163695.125
     1917945.504      163490.697
#Sta/Elev= 30
       0  2255.7    49.5 2230.49    59.4 2226.41    69.3 2225.77    89.1 2216.48
   158.4    2181   168.3 2180.86   178.2 2175.68     198  2167.6   247.5    2151
   257.4 2150.79   346.4 2123.94   425.6 2115.39   554.3 2112.65     557 2112.66
   564.2  2112.7     572 2114.21   593.9 2122.63   633.5 2130.65   653.3 2132.94
   663.2 2135.46     683  2141.8     732 2160.35   751.5 2163.85   761.2 2167.56
   770.9 2172.04   780.7 2177.99   829.4 2209.56   848.8 2209.85   907.2  2248.1
#Mann= 3 , 0 , 0
       0      .1       0     557    .045       0     572      .1       0
Bank Sta=557,572
XS Rating Curve= 0 ,0
Exp/Cntr=0.3,0.1

Type RM Length L Ch R = 1 ,25112   ,911,899.3,886.8
XS GIS Cut Line= 3
     1918558.063      164477.611     1918562.995      164068.329
     1918589.451      163446.891
#Sta/Elev= 30
       0  2338.3      30 2316.77    39.9 2315.27    79.9 2282.54   119.8 2247.35
   129.8 2240.11   139.8 2238.67   189.7 2196.35   219.6 2172.81   229.6 2166.47
   239.6 2165.34   279.5  2133.5   289.5  2127.1   319.5 2112.04   329.4 2111.48
   339.4 2107.81   401.8 2107.14   416.8 2107.01   537.7    2106   656.1  2107.9
   705.5 2126.38   715.4 2127.23   764.7 2137.86   833.8 2148.53   863.5 2156.65
   893.1 2168.71   932.6 2179.09  1001.7 2217.28  1021.4 2222.17  1031.3 2227.02
#Mann= 3 , 0 , 0
       0      .1       0   401.8    .045       0   416.8      .1       0
Bank Sta=401.8,416.8
XS Rating Curve= 0 ,0
Exp/Cntr=0.3,0.1

Type RM Length L Ch R = 1 ,24212.7 ,485.8,485.5,485.3
XS GIS Cut Line= 3
     1919595.041      164455.158     1919433.446      164155.331
     1918970.076      163327.885
#Sta/Elev= 30
       0 2291.27    58.4 2272.22    77.8 2270.75    97.3 2265.89     107 2267.98
   116.8 2266.17   155.7 2252.69   204.4 2226.18   223.8 2222.97   243.3 2211.72
   291.9 2176.33   321.1 2158.82   340.6 2153.41   420.5 2103.24   430.4  2098.4
   442.3 2097.71   457.3 2097.72   620.1 2097.67   769.9 2094.17   839.7 2101.08
  1009.4 2102.39  1029.4 2106.67  1039.4 2109.83  1109.3 2156.13  1129.2 2162.71
  1159.2 2181.31  1179.2 2187.99    1239 2228.53    1259 2236.33    1289 2256.41
#Mann= 3 , 0 , 0
       0     .06       0   442.3    .045       0   457.3     .06       0
Bank Sta=442.3,457.3
XS Rating Curve= 0 ,0
Exp/Cntr=0.3,0.1

Type RM Length L Ch R = 1 ,23726.9 ,523.7,510.4,497.2
XS GIS Cut Line= 3
      1919987.63      164182.115      1919866.92      163952.377
     1919442.489      163200.861
#Sta/Elev= 30
       0 2303.95      10 2301.78      20 2297.77    39.9 2282.44   109.8  2231.1
   119.8 2225.83   129.8 2222.79   189.6 2179.62   209.6 2162.45   219.6 2155.29
   229.6 2149.42   239.6 2148.81   269.4 2132.48     329 2103.47   338.9 2101.61
   358.7 2095.36   368.6 2093.97   470.4 2094.06   485.4 2093.95   517.4 2093.08
   537.3 2093.86     696 2094.46   864.7 2100.51   874.6  2101.5   884.5 2103.64
   914.3 2115.49   934.1  2119.4  1033.3 2154.59  1043.2 2155.52  1122.6 2190.81
#Mann= 3 , 0 , 0
       0     .06       0   470.4    .045       0   485.4     .06       0
Bank Sta=470.4,485.4
XS Rating Curve= 0 ,0
Exp/Cntr=0.3,0.1

Type RM Length L Ch R = 1 ,23216.7 ,325.9,324.2,322.5
XS GIS Cut Line= 2
     1920498.247      163664.078     1919540.527      163174.077
#Sta/Elev= 30
       0 2119.72      10 2114.37    19.9 2110.63    29.9  2107.9    39.8 2106.85
   119.5 2101.96   298.8 2089.27   348.6 2086.44   388.5 2085.38   390.5 2085.44
   405.5 2086.14   428.3 2088.53   438.3 2088.98   537.9 2091.56   597.7 2091.29
   737.1 2088.53   786.9  2088.7   816.8 2089.99   876.6 2093.64   886.5 2094.65
   926.4 2096.71   936.3 2098.48   946.3 2101.98   966.2  2111.2   976.2 2119.11
  1006.1 2134.29    1036  2150.9  1055.9 2162.55  1065.8 2170.33  1075.8  2173.2
#Mann= 3 , 0 , 0
       0     .06       0   390.5    .045       0   405.5     .06       0
Bank Sta=390.5,405.5
XS Rating Curve= 0 ,0
Exp/Cntr=0.3,0.1

Type RM Length L Ch R = 1 ,22892.3 ,467.4,479.8,492.2
XS GIS Cut Line= 3
     1920808.434      163412.968     1920533.917      163300.046
      1919478.68      162863.933
#Sta/Elev= 30
       0 2116.43    49.5  2110.4      99 2110.61   148.4  2106.6     277 2100.41
   326.6 2094.14   475.6 2090.11   525.2 2083.64   557.8 2081.59   564.9 2081.48
   572.8  2081.5   813.1 2084.11  1001.8 2091.33  1041.5 2094.63  1061.4  2102.2
  1091.1 2118.51  1101.1 2124.88    1111 2135.88  1140.8 2152.15  1180.5 2180.61
  1190.4 2188.45  1200.4 2200.71  1240.1 2231.68  1269.8 2265.51  1289.7 2290.55
  1309.6 2301.38  1359.2 2321.57  1369.1 2326.94  1398.9 2332.85  1438.6 2342.94
#Mann= 3 , 0 , 0
       0     .06       0   557.8    .045       0   572.8     .06       0
Bank Sta=557.8,572.8
XS Rating Curve= 0 ,0
Exp/Cntr=0.3,0.1

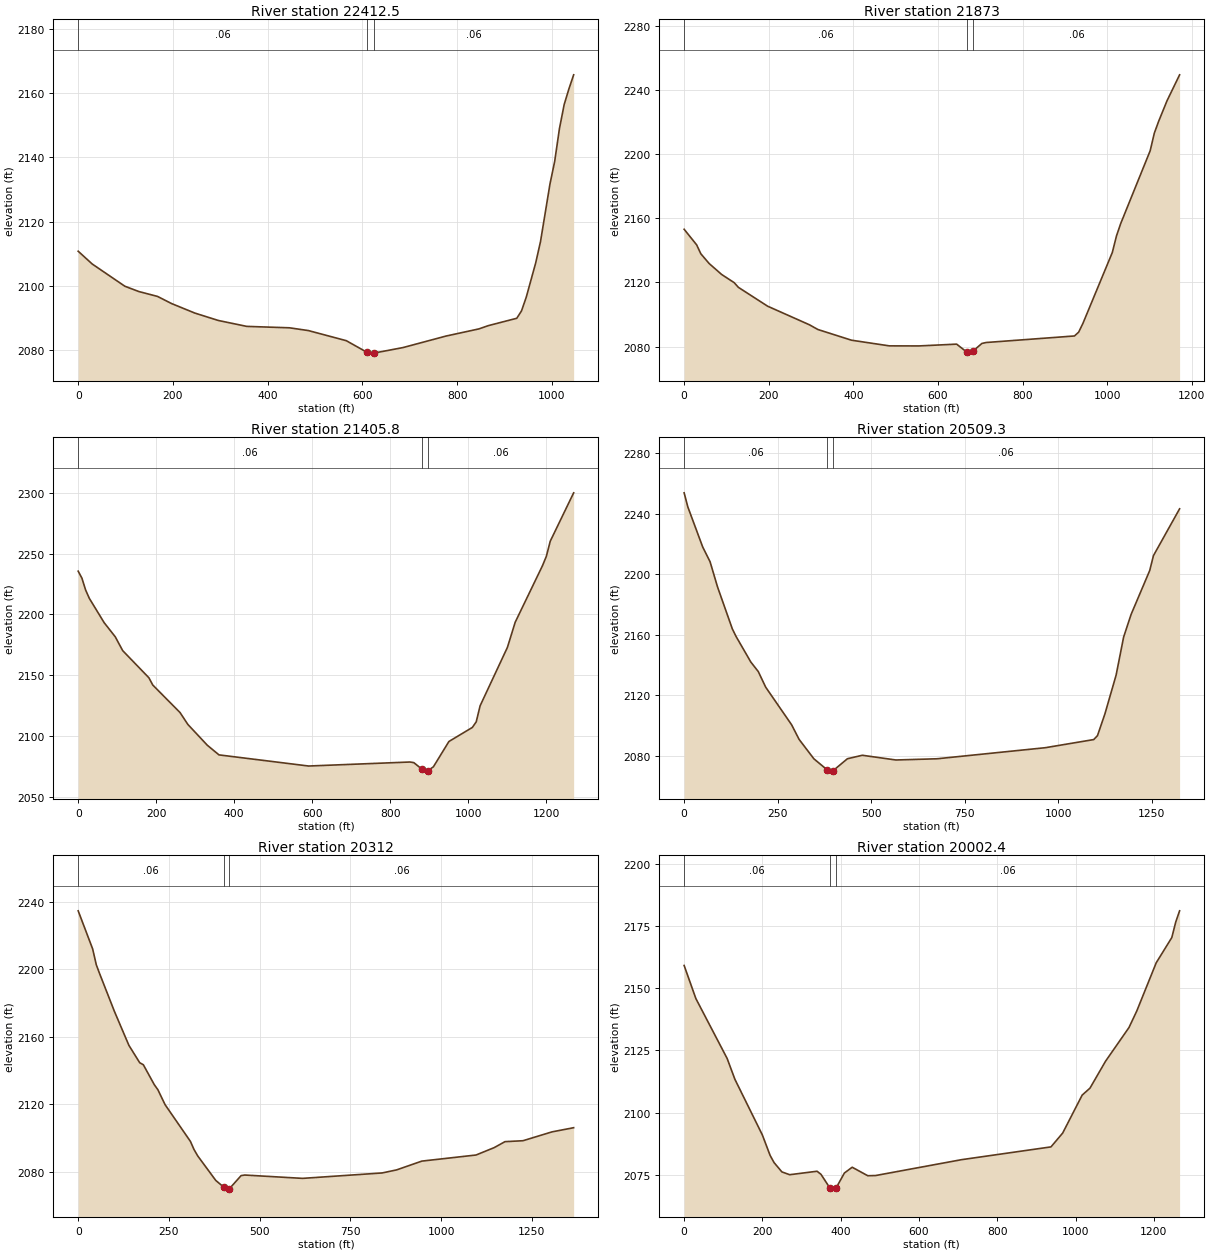
Type RM Length L Ch R = 1 ,22412.5 ,550.9,539.5,528
XS GIS Cut Line= 3
     1920751.518      163288.946     1920535.409      163117.616
     1920080.281      162496.587
#Sta/Elev= 30
       0 2110.74    29.6 2106.76    98.5 2099.83     128 2098.18   167.4 2096.66
     197 2094.44   246.2 2091.47   295.8 2089.16   355.8 2087.32   445.8 2086.88
   485.8 2086.02   565.8 2082.87     609 2079.29   615.8 2078.99     624    2079
   685.8 2080.73   775.8 2084.29   845.8 2086.54   865.7 2087.56   925.7 2089.85
   935.7 2092.17   945.7 2096.44   965.7 2107.16   975.7 2113.71   995.7 2131.66
  1005.7 2138.76  1015.7 2148.93  1025.7 2156.45  1035.7 2161.32  1045.7  2165.7
#Mann= 3 , 0 , 0
       0     .06       0     609    .045       0     624     .06       0
Bank Sta=609,624
XS Rating Curve= 0 ,0
Exp/Cntr=0.3,0.1

Type RM Length L Ch R = 1 ,21873   ,470,467,464.1
XS GIS Cut Line= 3
     1921185.684      162708.761     1920946.211      162591.945
     1920126.553      162208.399
#Sta/Elev= 30
       0 2153.14    29.6 2143.42    39.5 2137.86    59.2 2131.78    88.8 2124.95
   118.4 2119.86   128.3 2116.95   197.4 2105.21   296.3 2093.62   316.2 2090.69
   395.7 2084.02   485.2 2080.49   554.8 2080.45   644.3 2081.57   668.1 2076.66
   674.2 2075.97   683.1  2077.3     704    2082     714 2082.58   922.8 2086.66
   932.7 2089.01   942.7 2094.41  1012.3 2138.65  1022.2 2149.01  1032.2 2156.72
  1101.8 2202.03  1111.7 2213.08  1121.7 2220.27  1141.6 2233.15  1171.4 2249.35
#Mann= 3 , 0 , 0
       0     .06       0   668.1    .045       0   683.1     .06       0
Bank Sta=668.1,683.1
XS Rating Curve= 0 ,0
Exp/Cntr=0.3,0.1

Type RM Length L Ch R = 1 ,21405.8 ,893,896.5,897.8
XS GIS Cut Line= 3
     1921399.846      162243.444     1921238.251      162186.983
     1920190.802      161854.058
#Sta/Elev= 30
       0 2235.49     9.5 2229.83      19 2220.11    28.5 2213.23    66.6 2193.24
    95.1 2181.62   114.1 2170.29   181.2 2148.04   191.2 2142.06   261.1 2119.48
   281.1 2109.74     331 2092.65     361 2084.71   590.8 2075.57   850.6 2078.86
   860.6 2078.34   880.6 2073.17   890.6 2071.38   895.6  2071.6   910.6 2074.88
   950.5  2095.7  1010.5 2107.22  1020.5 2111.84  1030.5 2125.04  1100.4 2172.88
  1120.4 2193.57  1190.3 2239.94  1200.3 2247.72  1210.3  2260.1  1270.3 2299.82
#Mann= 3 , 0 , 0
       0     .06       0   880.6    .045       0   895.6     .06       0
Bank Sta=880.6,895.6
XS Rating Curve= 0 ,0
Exp/Cntr=0.3,0.1

Type RM Length L Ch R = 1 ,20509.3 ,198.6,197.3,198.4
XS GIS Cut Line= 3
     1921558.527      161835.038     1921217.491       161652.75
      1920344.61      161308.917
#Sta/Elev= 30
       0 2253.73     9.9 2244.41    49.6 2217.97    69.4 2208.16    89.2 2191.64
   128.9 2163.82   138.8 2158.85   178.5 2141.88   198.3 2135.62   218.1 2125.31
   287.5 2100.44   307.4 2090.83     347 2077.97   382.3 2070.74   396.7 2069.84
   397.3 2069.92   436.6 2078.02   476.5 2080.32   566.3  2077.2   676.1    2078
   965.6 2085.31  1095.3 2090.69  1105.3 2093.28  1125.2 2107.66  1155.2 2133.34
  1175.2 2158.39  1195.1 2173.31    1245 2202.39    1255 2212.24  1324.9 2243.17
#Mann= 3 , 0 , 0
       0     .06       0   382.3    .045       0   397.3     .06       0
Bank Sta=382.3,397.3
XS Rating Curve= 0 ,0
Exp/Cntr=0.3,0.1

Type RM Length L Ch R = 1 ,20312   ,306.3,309.6,312.7
XS GIS Cut Line= 3
     1921664.122      161634.872     1921289.936      161469.366
     1920418.593      161075.286
#Sta/Elev= 30
       0 2234.67    39.9 2212.05    49.9 2202.67    59.9 2196.94    99.8 2175.04
   139.7 2154.89   169.6 2144.54   179.6 2143.34   209.6 2131.58   219.6 2128.55
   239.5 2119.66   309.4 2097.85   319.3 2093.03   329.3 2089.31   379.2 2074.71
   401.7 2070.67   409.2 2069.56   416.7  2069.8     449 2077.58     459 2077.92
   618.4 2075.94   837.5 2079.15   877.4 2080.96   947.1 2086.18  1096.5  2089.8
  1146.3 2094.16  1176.2 2097.72    1226 2098.28  1305.7 2103.52  1365.5    2106
#Mann= 3 , 0 , 0
       0     .06       0   401.7    .045       0   416.7     .06       0
Bank Sta=401.7,416.7
XS Rating Curve= 0 ,0
Exp/Cntr=0.3,0.1

Type RM Length L Ch R = 1 ,20002.4 ,486.7,490.4,492.7
XS GIS Cut Line= 3
     1921725.072      161384.226     1921377.226      161168.139
     1920630.809      160748.201
#Sta/Elev= 30
       0  2159.2      30 2145.87   109.9 2121.76   129.8 2113.35   199.8 2091.01
   219.7 2082.74   229.7 2079.88   249.7 2076.12   269.7 2074.98   339.6 2076.38
   349.6 2075.15   373.1 2069.47   379.5 2069.18   388.1 2069.59   409.5 2075.67
   429.4 2077.99   469.2 2074.57   489.2 2074.65   708.3 2081.02   937.3 2086.18
   967.2 2091.75    1017 2107.03  1036.9 2109.82  1076.7 2120.66  1136.5  2134.2
  1156.4 2140.84  1206.2 2160.29    1246 2170.43    1256 2176.66  1265.9 2181.19
#Mann= 3 , 0 , 0
       0     .06       0   373.1    .045       0   388.1     .06       0
Bank Sta=373.1,388.1
XS Rating Curve= 0 ,0
Exp/Cntr=0.3,0.1

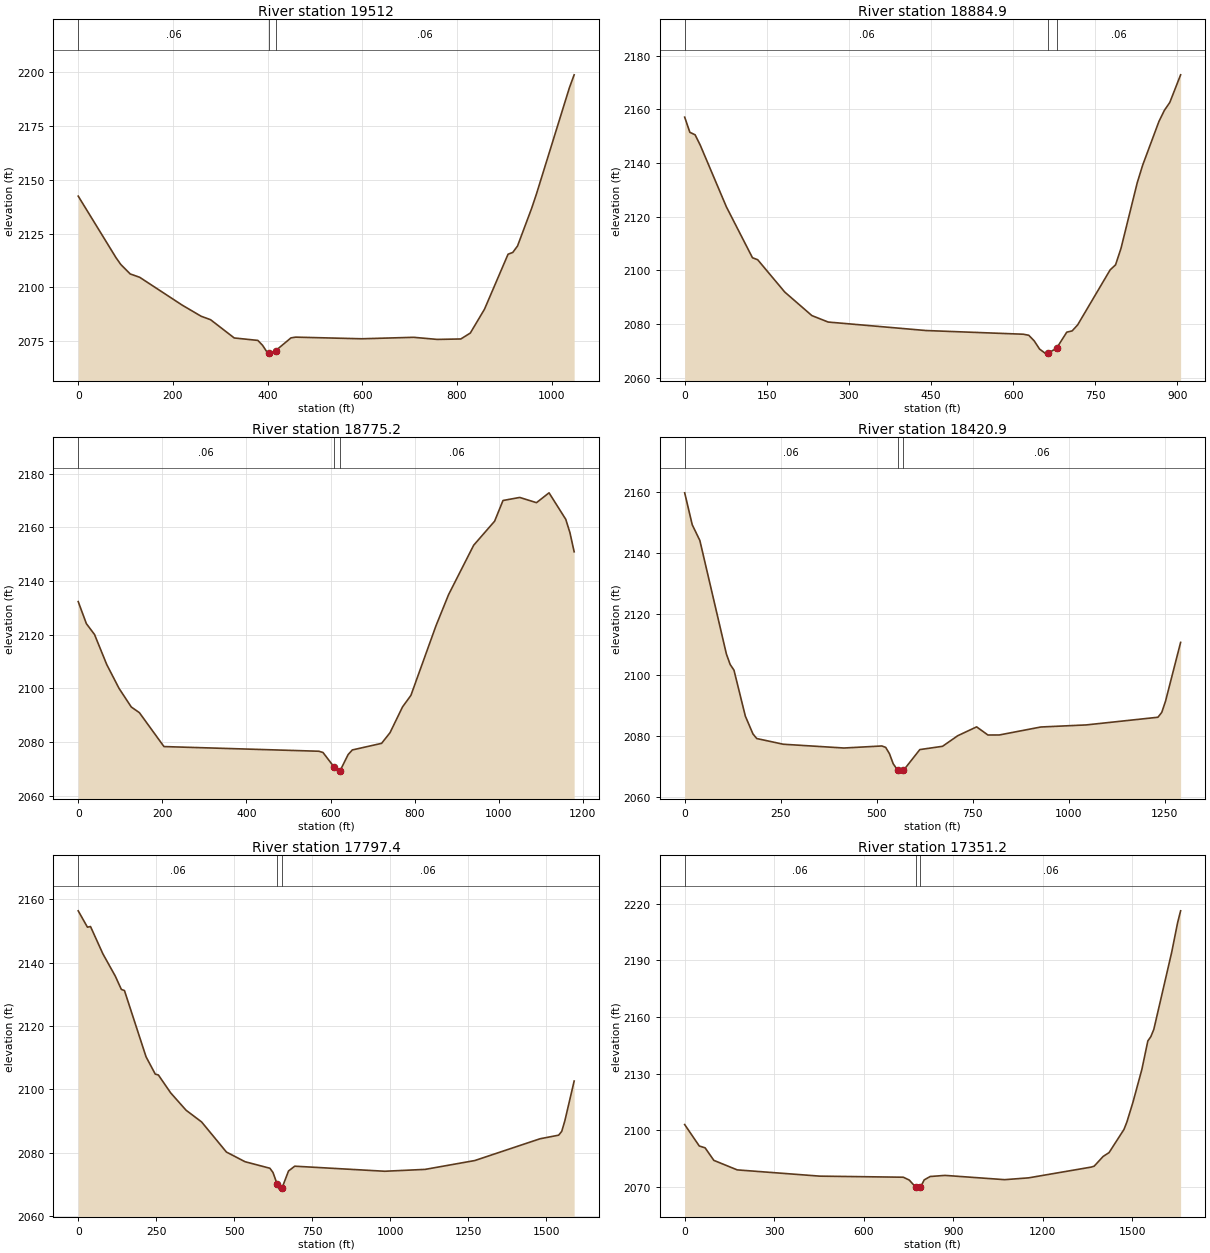
Type RM Length L Ch R = 1 ,19512   ,616.5,627.1,639
XS GIS Cut Line= 3
     1921992.411      161054.088     1921683.764      160785.125
     1921179.843       160393.86
#Sta/Elev= 30
       0 2142.46    79.9 2113.78    89.9 2110.65   109.8 2106.24   129.8 2104.68
   219.7 2091.71   259.6 2086.55   279.6 2084.93   329.5 2076.44   379.4  2075.3
   389.4    2073   399.4 2069.66   401.9 2069.59   409.4 2069.38   416.9 2070.51
   449.3 2076.47   459.2 2076.82   598.8 2076.06   708.4 2076.74   758.3 2075.76
   808.1 2075.97   828.1 2078.73     858  2089.8   907.8 2115.41   917.8 2116.25
   927.8 2119.24   957.7 2136.82   967.6 2143.33  1037.4 2192.92  1047.4 2198.91
#Mann= 3 , 0 , 0
       0     .06       0   401.9    .045       0   416.9     .06       0
Bank Sta=401.9,416.9
XS Rating Curve= 0 ,0
Exp/Cntr=0.3,0.1

Type RM Length L Ch R = 1 ,18884.9 ,110.5,109.7,108.9
XS GIS Cut Line= 3
     1922252.602      160898.115     1922188.353      160781.299
     1921890.439       160068.69
#Sta/Elev= 30
       0 2157.04     9.5 2151.39      19 2150.48    28.6 2146.54    76.2 2123.62
   123.8 2104.68   133.3 2103.94   182.8 2091.89   232.3 2083.13     262 2080.73
   440.3 2077.57   618.5 2076.19   628.4  2075.8   638.3 2073.72   648.2 2070.64
   658.1 2069.15   664.2 2069.19   679.2 2070.98   697.8 2076.96   707.6 2077.43
   717.6 2079.65     777 2100.16   786.9 2102.04   796.8 2108.16   826.5 2132.64
   836.4 2139.17   866.1 2155.44     876 2159.56   885.9 2162.51   905.7 2172.81
#Mann= 3 , 0 , 0
       0     .06       0   664.2    .045       0   679.2     .06       0
Bank Sta=664.2,679.2
XS Rating Curve= 0 ,0
Exp/Cntr=0.3,0.1

Type RM Length L Ch R = 1 ,18775.2 ,345,354.2,363.3
XS GIS Cut Line= 3
     1922316.851       160812.45     1922258.443      160627.491
      1921847.64      159731.903
#Sta/Elev= 30
       0 2132.31    19.4  2124.1    38.8 2120.05    67.9 2108.84      97    2100
   126.1 2093.05   145.5 2090.92   203.9 2078.29   572.2 2076.55   582.1 2076.08
     608 2070.77   621.9 2069.14     623 2069.37   641.8  2075.3   651.8 2077.03
   721.4 2079.49   741.4 2083.45   771.2 2093.07   791.1 2097.36   850.8 2123.33
   880.7 2134.91   940.4 2153.32   990.2 2162.28  1010.1 2169.98  1049.9 2171.12
  1089.7 2169.17  1119.6 2172.84  1159.4 2162.95  1169.3 2157.98  1179.3 2150.88
#Mann= 3 , 0 , 0
       0     .06       0     608    .045       0     623     .06       0
Bank Sta=608,623
XS Rating Curve= 0 ,0
Exp/Cntr=0.3,0.1

Type RM Length L Ch R = 1 ,18420.9 ,637.8,623.4,608.9
XS GIS Cut Line= 3
     1922410.304      160814.397     1922398.622      160103.767
     1922400.569      159523.582
#Sta/Elev= 30
       0 2159.87    19.7 2149.38    39.5 2144.22   108.6 2106.94   118.4 2103.51
   128.3 2101.65   157.9 2086.56   177.7 2080.71   187.6 2079.19   256.6 2077.32
   414.6 2076.08   513.3 2076.75   523.2 2076.29     533 2074.22   542.9 2070.88
   554.5 2068.79   562.7 2068.49   569.5 2068.74     612 2075.56   671.2 2076.64
   710.7 2080.11   759.9 2083.02   789.4 2080.35   818.9 2080.36   927.1 2082.98
  1045.1 2083.66  1231.9 2086.18  1241.8 2087.78  1251.6 2091.45  1290.9 2110.76
#Mann= 3 , 0 , 0
       0     .06       0   554.5    .045       0   569.5     .06       0
Bank Sta=554.5,569.5
XS Rating Curve= 0 ,0
Exp/Cntr=0.3,0.1

Type RM Length L Ch R = 1 ,17797.4 ,451.3,446.1,440.9
XS GIS Cut Line= 3
     1923303.945      160835.813     1923161.819      160498.994
     1922402.516      159539.157
#Sta/Elev= 30
       0 2156.32    29.6 2151.16    39.5 2151.36      79 2142.76   118.6 2135.76
   138.3 2131.52   148.2 2131.16   217.4 2110.26     247 2104.78   256.9 2104.52
   296.4 2098.86   345.8 2093.38   395.4  2089.7     475 2080.19   534.7 2077.14
   614.3 2075.08   624.3 2073.73   637.9 2069.99   644.2 2068.49   652.9 2068.77
     674 2074.21   693.9 2075.73   982.5 2074.13  1111.8 2074.72    1271 2077.51
    1480 2084.38  1539.7 2085.52  1549.6 2086.71  1559.6 2090.06  1589.4  2102.6
#Mann= 3 , 0 , 0
       0     .06       0   637.9    .045       0   652.9     .06       0
Bank Sta=637.9,652.9
XS Rating Curve= 0 ,0
Exp/Cntr=0.3,0.1

Type RM Length L Ch R = 1 ,17351.2 ,1629.9,1628.2,1633.9
XS GIS Cut Line= 3
     1923710.854      160454.215     1923486.956      160249.787
     1922461.052      159357.801
#Sta/Elev= 30
       0 2103.05    48.9  2091.7    68.5 2090.71    97.8 2084.07     176 2079.03
   453.1 2075.71     733 2075.14     753 2073.62   775.1 2069.79     783 2068.83
   790.1 2069.75     803 2073.73     823 2075.52     873 2076.11  1072.9 2073.84
  1152.8  2074.8  1362.8 2080.51  1372.8    2081  1402.7 2086.13  1422.7 2088.18
  1472.7 2100.47  1482.7  2104.5  1502.7 2114.81  1532.7 2132.28  1552.7 2147.36
  1562.7 2149.62  1572.7 2153.46  1632.6  2194.3  1652.6 2210.08  1662.6 2216.32
#Mann= 3 , 0 , 0
       0     .06       0   775.1    .045       0   790.1     .06       0
Bank Sta=775.1,790.1
XS Rating Curve= 0 ,0
Exp/Cntr=0.3,0.1

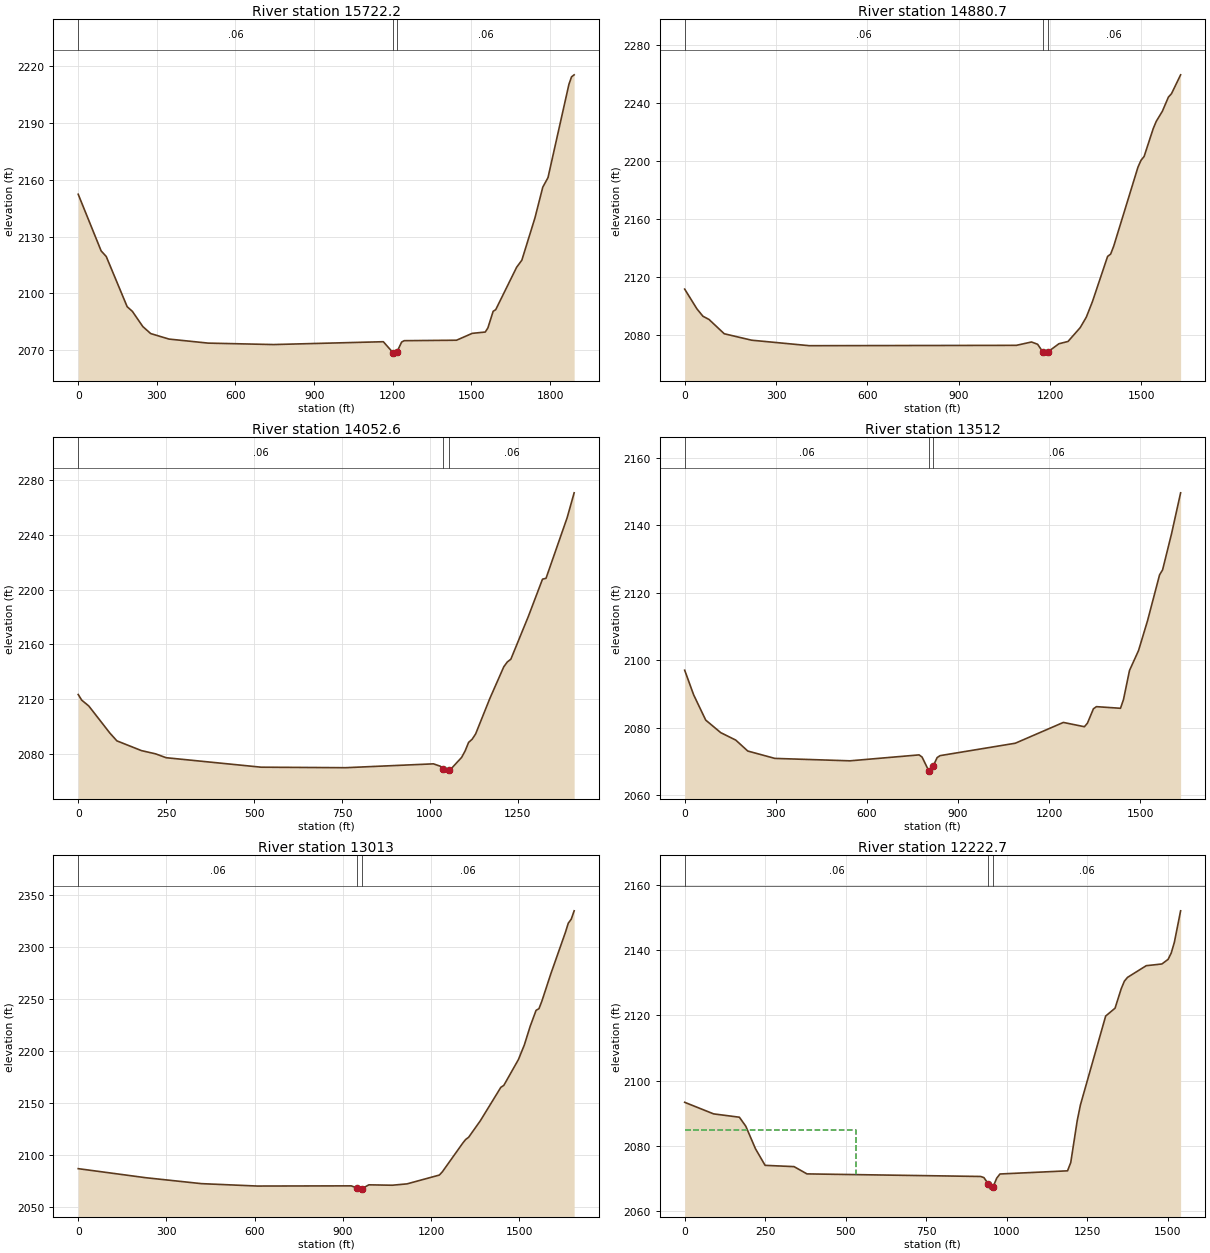
Type RM Length L Ch R = 1 ,15722.2 ,827.6,841.4,854.3
XS GIS Cut Line= 3
     1923762.123      160612.889     1923751.739      160506.457
     1923452.492       158746.77
#Sta/Elev= 30
       0 2152.38    87.5 2122.43   106.9 2119.49   186.7 2092.95   206.7 2090.47
   246.5 2082.44   276.5 2078.74   346.3 2075.83   495.8 2073.69   745.1 2072.93
    1164 2074.43  1201.2 2068.58  1203.8  2068.4  1216.2  2069.1  1233.8 2074.25
  1243.7 2074.98  1443.2 2075.22    1503 2078.85  1552.8 2079.55  1562.8 2081.72
  1582.8 2090.47  1592.7 2091.38  1672.5 2113.79  1692.4 2117.54  1742.3 2139.87
  1772.2 2156.11  1792.2 2161.21  1871.9 2210.44  1881.9 2214.44  1891.9 2215.51
#Mann= 3 , 0 , 0
       0     .06       0  1201.2    .045       0  1216.2     .06       0
Bank Sta=1201.2,1216.2
XS Rating Curve= 0 ,0
Exp/Cntr=0.3,0.1

Type RM Length L Ch R = 1 ,14880.7 ,829.9,828,826.1
XS GIS Cut Line= 3
      1923769.91      160483.094     1923755.002      160343.981
     1924231.982      158933.337
#Sta/Elev= 30
       0  2111.7      40 2098.13      60 2092.96      80 2090.74   129.9 2080.89
   219.9 2076.43   409.8 2072.64  1089.3 2072.88  1139.3  2075.2  1159.3 2073.61
  1177.3 2068.06  1179.3 2067.51  1192.3 2068.25  1229.2 2073.98  1259.2 2075.57
  1299.2 2085.12  1319.2 2092.33  1339.2 2102.97  1389.2 2134.28  1399.2 2135.87
  1409.1 2141.28  1489.1 2196.01  1499.1 2200.67  1509.1 2203.26  1539.1 2222.55
  1549.1 2227.56    1569 2234.45    1589 2244.26    1599 2246.58    1629 2259.61
#Mann= 3 , 0 , 0
       0     .06       0  1177.3    .045       0  1192.3     .06       0
Bank Sta=1177.3,1192.3
XS Rating Curve= 0 ,0
Exp/Cntr=0.3,0.1

Type RM Length L Ch R = 1 ,14052.6 ,538.2,540.6,542.8
XS GIS Cut Line= 2
     1924494.169       160644.04     1924813.465      159270.805
#Sta/Elev= 30
       0 2123.22      10 2119.08      30 2114.84      90    2095     110 2089.28
     180 2082.13     220 2079.78     250 2076.94     520 2070.01   759.9 2069.64
  1009.9 2072.46  1029.9 2070.67  1037.9 2068.51  1049.9 2067.13  1052.9 2067.62
  1059.9 2068.78  1089.9 2077.15  1099.9 2081.88  1109.9 2088.18  1119.9 2090.46
  1129.9  2094.4  1169.9 2120.12  1209.9 2143.53  1219.9 2147.05  1229.9 2149.03
  1279.9  2180.5  1319.9 2207.63  1329.9 2208.26  1389.9 2252.56  1409.9 2270.84
#Mann= 3 , 0 , 0
       0     .06       0  1037.9    .045       0  1052.9     .06       0
Bank Sta=1037.9,1052.9
XS Rating Curve= 0 ,0
Exp/Cntr=0.3,0.1

Type RM Length L Ch R = 1 ,13512   ,497.3,498.9,500.7
XS GIS Cut Line= 3
     1924834.233      160654.424     1925108.118      159890.514
     1925379.373       159115.05
#Sta/Elev= 30
       0 2097.05    29.7 2089.73    69.3 2082.28   118.8 2078.56   168.2 2076.36
   207.8 2073.12   296.9 2070.94   544.3 2070.22   771.9 2071.98   781.8 2071.33
     804 2067.22   811.5 2067.17     819 2068.81   831.3 2071.18   841.2 2071.76
  1088.7 2075.43    1247 2081.59  1316.3 2080.32  1326.2 2081.36    1346 2085.63
  1355.9 2086.26  1435.1 2085.78    1445 2088.37  1464.8 2096.98  1494.5 2102.87
  1524.2 2111.72  1563.8 2125.29  1573.7 2126.76  1603.4 2137.53  1633.1 2149.58
#Mann= 3 , 0 , 0
       0     .06       0     804    .045       0     819     .06       0
Bank Sta=804,819
XS Rating Curve= 0 ,0
Exp/Cntr=0.3,0.1

Type RM Length L Ch R = 1 ,13013   ,783.9,790.3,796.6
XS GIS Cut Line= 3
     1925109.399      160854.309     1925633.772      159732.877
     1925885.576      159361.662
#Sta/Elev= 30
       0 2086.46   229.6 2077.74   419.3 2072.02     609 2069.71   928.5 2069.89
   949.7 2067.69   958.4 2066.74   964.7 2067.21   988.4 2070.88  1068.2  2070.5
  1118.2  2071.8    1228 2080.29    1238 2083.29  1307.8 2111.12  1317.7 2114.61
  1327.7 2116.72  1367.6 2132.68  1437.3 2164.86  1447.3  2166.7  1497.1 2191.66
  1517.1 2205.66    1537 2223.63    1557 2239.01  1566.9 2240.63  1576.9 2248.02
  1606.8  2273.9  1656.6 2313.98  1666.6 2323.02  1676.6 2326.84  1686.5 2334.89
#Mann= 3 , 0 , 0
       0     .06       0   949.7    .045       0   964.7     .06       0
Bank Sta=949.7,964.7
XS Rating Curve= 0 ,0
Exp/Cntr=0.3,0.1

Type RM Length L Ch R = 1 ,12222.7 ,449.8,451.6,453.4
XS GIS Cut Line= 3
     1925337.839      161246.291     1926163.338      160296.189
     1926352.839      160088.516
#Sta/Elev= 30
       0 2093.33    89.9 2089.78   169.8 2088.76   189.8 2085.99   219.8 2079.09
   249.7    2074   339.6 2073.61   379.6 2071.38     919 2070.59     929 2070.25
   942.1 2068.39     949 2066.71   957.1  2067.3   968.9 2070.08   978.9 2071.35
  1188.7 2072.32  1198.7 2074.87  1218.7 2087.67  1228.7 2092.52  1307.1 2119.78
  1336.2 2122.18  1355.6 2128.22  1365.3 2130.49    1375 2131.64  1433.1 2135.22
  1481.6 2135.74    1501 2137.16  1510.7 2139.11  1520.4  2142.4  1539.8 2152.04
#Mann= 3 , 0 , 0
       0     .06       0   942.1    .045       0   957.1     .06       0
#XS Ineff= 2 , 0
          531.83 2084.76
Permanent Ineff=
       F       F
Bank Sta=942.1,957.1
XS Rating Curve= 0 ,0
Exp/Cntr=0.3,0.1

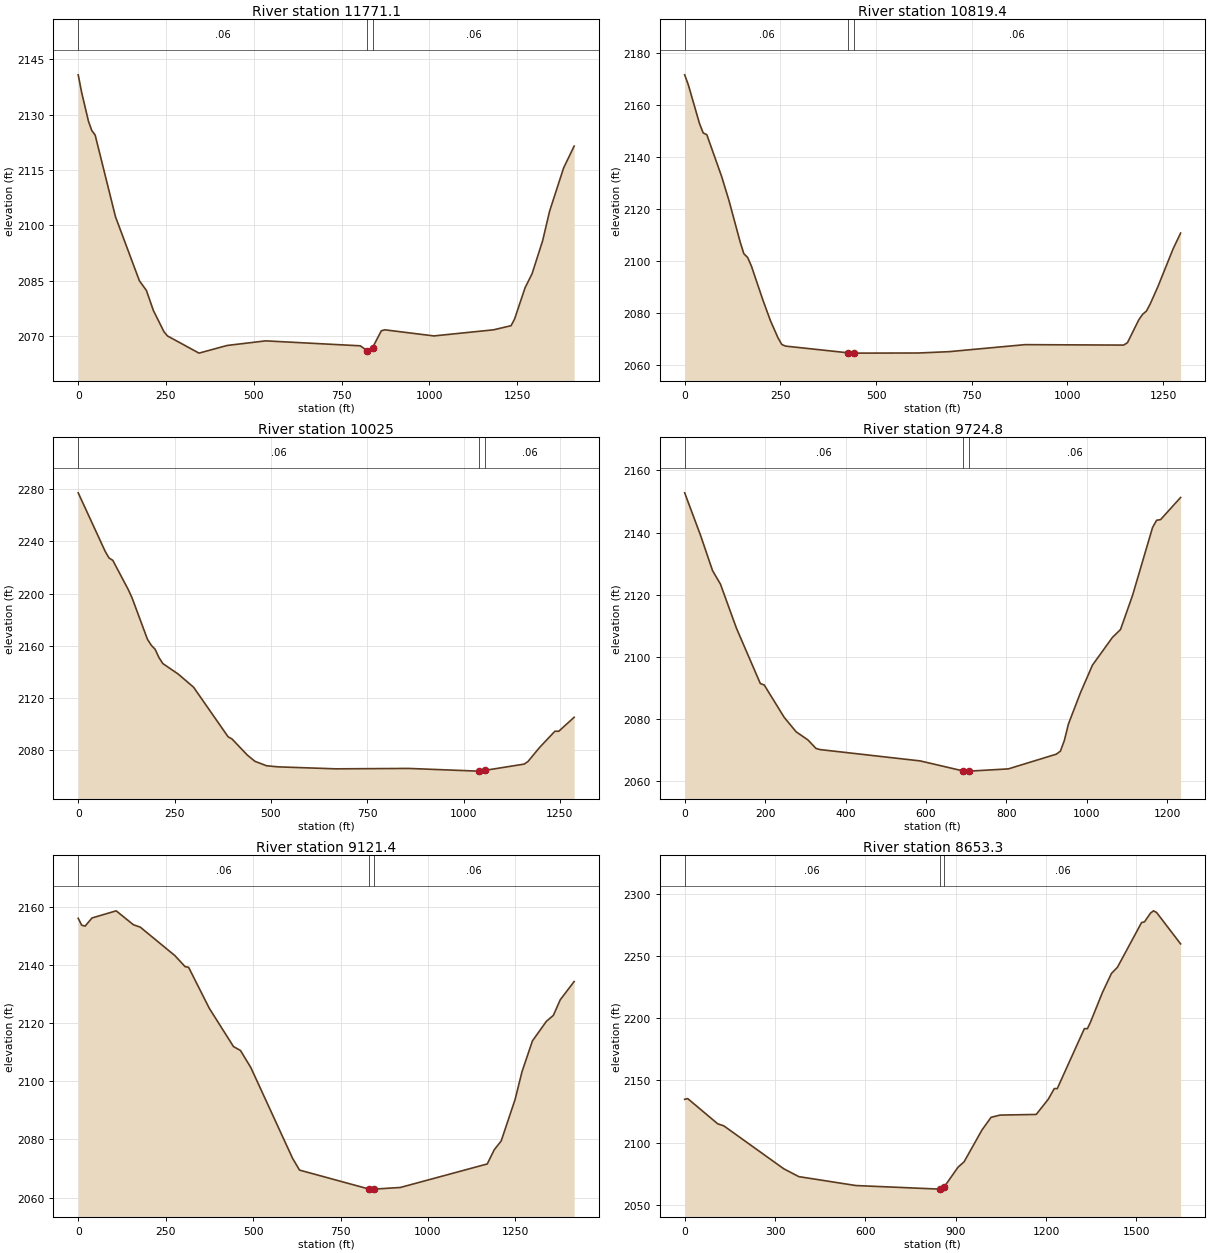
Type RM Length L Ch R = 1 ,11771.1 ,960.6,950.7,940.7
XS GIS Cut Line= 3
      1925654.54      161440.984     1925781.739      161337.148
     1926672.136      160462.327
#Sta/Elev= 30
       0  2140.8     9.7 2136.08      29  2128.3    38.6 2125.73    48.3 2124.48
   106.2 2102.36   174.2 2085.05   194.2 2082.41   214.1 2076.98   244.1 2071.26
   254.1  2070.1     344 2065.44   423.8 2067.51   533.7 2068.76   803.3 2067.42
   823.3  2066.1   833.3 2066.06   838.3 2066.93   863.2 2071.48   873.2 2071.75
    1013  2070.1  1182.8 2071.75  1232.7 2072.87  1242.7 2074.66  1272.6 2083.14
  1292.6 2086.95  1322.6 2095.86  1342.5 2103.88  1382.5 2115.62  1412.4  2121.5
#Mann= 3 , 0 , 0
       0     .06       0   823.3    .045       0   838.3     .06       0
Bank Sta=823.3,838.3
XS Rating Curve= 0 ,0
Exp/Cntr=0.3,0.1

Type RM Length L Ch R = 1 ,10819.4 ,809.9,794.5,777.7
XS GIS Cut Line= 3
      1926326.88      161861.521     1926391.778      161721.342
     1926822.698      160664.808
#Sta/Elev= 30
       0 2171.79     9.6 2167.92    38.6 2153.12    48.3 2149.46    57.9 2148.74
    96.6 2132.67   115.8  2123.4   144.8 2107.58   154.5    2103   164.4 2101.55
   174.3 2098.24   204.1 2085.28   223.9 2077.28   243.8 2070.63   253.7 2068.08
   263.6 2067.45   426.5 2064.88   441.5 2064.75   610.9  2064.8   690.3 2065.31
   888.7 2068.01  1146.7 2067.84  1156.6 2068.76  1186.4 2077.61  1196.3 2079.68
  1206.2 2080.94  1216.1 2083.67    1236 2090.27  1275.7  2104.8  1295.5 2110.93
#Mann= 3 , 0 , 0
       0     .06       0   426.5    .045       0   441.5     .06       0
Bank Sta=426.5,441.5
XS Rating Curve= 0 ,0
Exp/Cntr=0.3,0.1

Type RM Length L Ch R = 1 ,10025   ,310.6,300.9,292.6
XS GIS Cut Line= 2
     1927381.003      161900.595     1926882.404       160714.13
#Sta/Elev= 30
       0  2277.1    69.8 2232.42    79.8 2227.28    89.8 2225.39   129.7 2203.13
   139.7 2196.72   179.6 2165.04   189.6 2160.39   199.5 2157.36   209.5 2151.04
   219.5 2146.41   259.4 2138.37   299.3 2128.31   389.1 2090.27   399.1 2088.66
     439 2076.28   458.9  2071.5   488.8 2068.14   518.8  2067.3   668.4 2065.78
     858 2066.09  1037.6 2064.03  1040.2 2064.09  1055.2 2064.61  1157.3 2069.41
  1167.2  2071.4  1197.2 2082.12  1237.1 2094.57  1247.1 2094.56    1287 2105.26
#Mann= 3 , 0 , 0
       0     .06       0  1040.2    .045       0  1055.2     .06       0
Bank Sta=1040.2,1055.2
XS Rating Curve= 0 ,0
Exp/Cntr=0.3,0.1

Type RM Length L Ch R = 1 ,9724.8  ,603.4,602.5,601
XS GIS Cut Line= 3
     1927554.744      161604.526     1927396.394      161318.976
     1926977.552      160514.867
#Sta/Elev= 30
       0 2152.81    39.6 2139.08    69.3 2127.77      89  2123.4   128.6 2109.26
     188 2091.43   197.9 2090.92   247.4 2080.53     277 2075.88   306.7 2073.22
   326.5 2070.51   336.5 2070.14   585.6 2066.49   693.1 2063.24   705.1  2063.2
   708.1  2063.2   804.8 2063.92   924.3 2068.67   934.3 2069.65   944.2 2073.11
   954.2 2078.36   984.1 2088.43    1014 2097.34  1063.8 2106.28  1083.7 2108.78
  1113.6 2119.76  1163.4 2141.64  1173.4 2143.97  1183.4 2144.19  1233.2 2151.32
#Mann= 3 , 0 , 0
       0     .06       0   693.1    .045       0   708.1     .06       0
Bank Sta=693.1,708.1
XS Rating Curve= 0 ,0
Exp/Cntr=0.3,0.1

Type RM Length L Ch R = 1 ,9121.4  ,462.4,468.1,473.6
XS GIS Cut Line= 3
     1928180.358      161376.086     1927881.829      161074.961
     1927134.397      160419.946
#Sta/Elev= 30
       0 2156.05     9.9  2153.7    19.7 2153.37    39.4 2156.17   108.5 2158.63
   157.8 2153.84   177.5 2153.01   276.1 2143.26   305.7 2139.42   315.6  2139.2
   374.7 2125.11   443.9 2111.94   463.8  2110.6   493.6  2104.7   612.8 2073.51
   632.7 2069.45     830 2062.97   841.4  2062.9     845  2062.9   920.9 2063.47
  1169.4 2071.56  1189.3 2076.43  1209.2 2079.47  1248.9 2093.73  1268.8 2103.32
  1298.6 2113.91  1338.4 2120.62  1358.2 2122.65  1378.1 2128.04  1417.8 2134.32
#Mann= 3 , 0 , 0
       0     .06       0     830    .045       0     845     .06       0
Bank Sta=830,845
XS Rating Curve= 0 ,0
Exp/Cntr=0.3,0.1

Type RM Length L Ch R = 1 ,8653.3  ,1402.9,1425.1,1445.9
XS GIS Cut Line= 3
     1928068.734       161158.03     1927542.474      160298.935
     1927606.663      159662.787
#Sta/Elev= 30
       0 2134.87      10 2135.49   109.7 2115.24   129.7 2113.64   329.2 2079.12
     379 2072.85   568.6  2065.7   846.9 2062.82   861.9 2064.68   907.7 2080.42
   927.7 2084.72   987.5 2110.39  1017.5 2120.45  1047.4 2122.24  1167.3 2122.74
  1207.3 2134.95  1227.3  2143.5  1237.2  2143.5  1327.2  2191.6  1337.2 2191.57
  1347.1 2196.56  1387.1 2220.54  1417.1 2235.88    1437 2240.84    1517 2276.67
    1527 2277.32  1546.9 2284.32  1556.9 2286.13  1566.9 2284.83  1646.8 2259.59
#Mann= 3 , 0 , 0
       0     .06       0   846.9    .045       0   861.9     .06       0
Bank Sta=846.9,861.9
XS Rating Curve= 0 ,0
Exp/Cntr=0.3,0.1

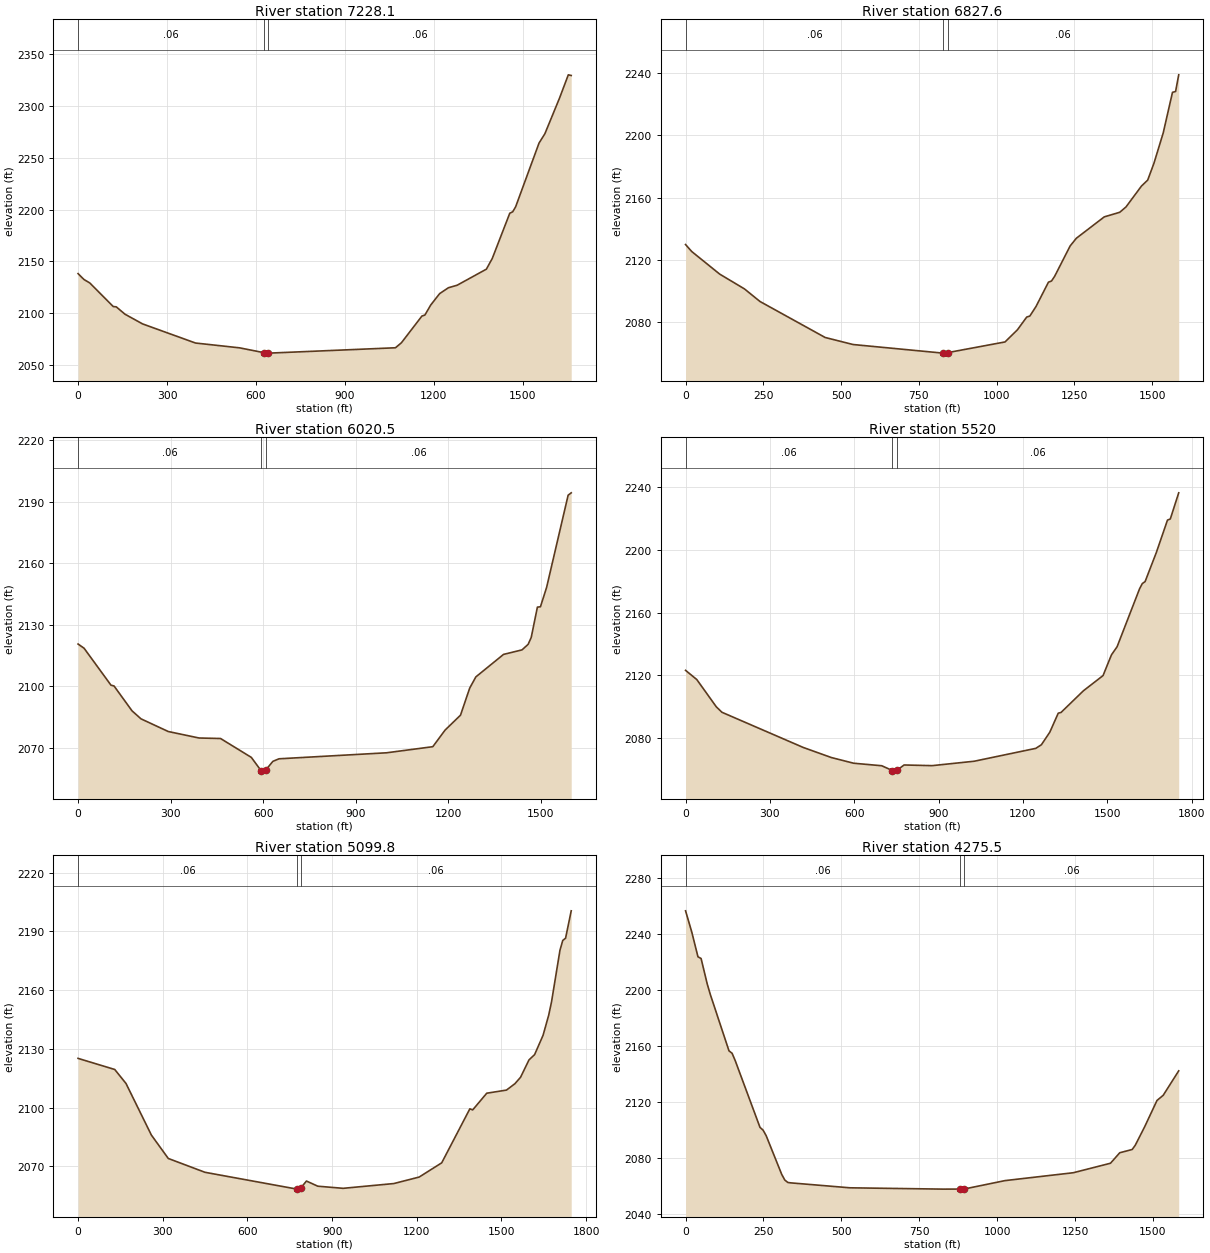
Type RM Length L Ch R = 1 ,7228.1  ,401.4,400.5,399.7
XS GIS Cut Line= 4
      1928141.42      161183.989     1928221.893      160888.056
     1928540.167      160032.958     1928439.949      159600.485
#Sta/Elev= 30
       0 2138.25    19.8 2132.61    39.6 2129.21   118.7 2106.45   128.6  2106.2
   158.3 2099.06   217.6 2089.69   395.9 2071.25   544.7 2066.59   626.7 2061.93
   641.7  2061.5   643.9 2061.49  1070.3 2066.66  1090.2 2071.44  1159.6  2097.3
  1169.5 2098.24  1189.3 2107.96  1219.1  2118.9  1248.7  2124.6  1278.3 2127.05
  1376.9 2142.56  1396.7 2152.84  1455.8 2196.58  1465.7 2197.97  1475.6 2202.81
  1554.5 2264.32  1574.2 2273.32  1623.6 2307.75  1653.2  2330.2    1663 2329.56
#Mann= 3 , 0 , 0
       0     .06       0   626.7    .045       0   641.7     .06       0
Bank Sta=626.7,641.7
XS Rating Curve= 0 ,0
Exp/Cntr=0.3,0.1

Type RM Length L Ch R = 1 ,6827.6  ,816.8,806.7,796.5
XS GIS Cut Line= 2
     1928458.986       161306.43     1928922.788      159790.419
#Sta/Elev= 30
       0 2129.95    19.9 2125.47   109.7    2111   189.4  2101.5   239.3 2093.43
   448.7 2070.35   538.4 2065.83   827.6 2060.31   828.2 2060.32   843.2 2060.65
    1027 2067.48  1066.9 2075.27  1096.8 2083.45  1106.8 2084.09  1126.7 2090.24
  1166.6 2105.81  1176.6  2106.6  1186.5 2109.56  1236.4 2129.06  1256.3 2133.99
  1346.1 2147.71  1395.9 2150.66  1415.9 2154.07  1465.7 2167.48  1485.7  2171.3
  1505.6    2182  1535.5 2201.49  1565.4 2227.59  1575.4 2228.14  1585.4 2238.82
#Mann= 3 , 0 , 0
       0     .06       0   828.2    .045       0   843.2     .06       0
Bank Sta=828.2,843.2
XS Rating Curve= 0 ,0
Exp/Cntr=0.3,0.1

Type RM Length L Ch R = 1 ,6020.5  ,502.4,500.4,498.3
XS GIS Cut Line= 3
     1929334.672      161476.029     1929293.138      161226.822
     1929123.538      159890.794
#Sta/Elev= 30
       0 2120.63    19.4  2118.6   106.9 2100.57   116.6 2100.22   174.9 2088.12
   204.1  2084.2   292.6 2078.03   392.3 2074.88   462.1 2074.63   561.9 2065.44
   593.9 2058.89   601.8 2058.75   608.9 2059.32   631.7  2063.5   651.7 2064.75
  1000.8 2067.68  1150.5 2070.65  1190.4 2078.75  1240.3 2085.99  1270.2 2099.19
  1290.1 2104.63  1379.9 2115.58  1439.8 2117.78  1459.7  2120.5  1469.7 2123.84
  1489.7  2138.6  1499.6 2138.78  1519.6 2148.22  1589.4 2193.09  1599.4 2194.25
#Mann= 3 , 0 , 0
       0     .06       0   593.9    .045       0   608.9     .06       0
Bank Sta=593.9,608.9
XS Rating Curve= 0 ,0
Exp/Cntr=0.3,0.1

Type RM Length L Ch R = 1 ,5520    ,420.7,420.5,420.2
XS GIS Cut Line= 2
     1929829.625      161403.343     1929504.271       159679.66
#Sta/Elev= 30
       0 2123.25    39.9  2117.4   109.6 2099.96   129.6 2096.52   418.6 2074.12
   518.3 2067.71     598 2064.07   697.7 2062.47   735.6 2059.43   747.5 2059.04
   750.6 2059.46   777.4 2062.96   877.1 2062.53  1026.6 2065.34  1245.8 2073.55
  1265.8 2075.87  1295.7 2083.88  1325.6 2095.96  1335.5 2096.42  1415.3 2110.26
    1485 2119.92  1514.9 2133.13  1534.9 2138.28  1614.6  2175.1  1624.6 2178.56
  1634.5 2179.78  1674.4 2198.27  1714.2 2218.99  1724.2  2219.7  1754.1 2236.36
#Mann= 3 , 0 , 0
       0     .06       0   735.6    .045       0   750.6     .06       0
Bank Sta=735.6,750.6
XS Rating Curve= 0 ,0
Exp/Cntr=0.3,0.1

Type RM Length L Ch R = 1 ,5099.8  ,822,824.2,826.4
XS GIS Cut Line= 3
     1930227.664      161344.503     1930037.298      160313.062
     1929722.328      159690.044
#Sta/Elev= 30
       0 2125.15   129.9 2119.48   169.8 2112.33   259.7 2085.98   319.6 2074.02
   449.5 2066.96   774.6 2058.39   779.2 2058.36   789.6 2059.08   809.1 2062.49
   849.1 2059.86     939 2058.77  1118.7 2061.21  1208.4 2064.53  1288.2 2071.79
  1387.9 2099.38  1397.9 2098.82  1447.8 2107.36  1517.6 2108.95  1547.5 2112.21
  1567.5  2115.5  1597.4 2124.37  1617.3 2127.08  1647.2 2136.91  1667.2 2147.22
  1677.2 2153.98  1707.1 2180.37    1717 2185.39    1727 2186.55    1747 2200.53
#Mann= 3 , 0 , 0
       0     .06       0   774.6    .045       0   789.6     .06       0
Bank Sta=774.6,789.6
XS Rating Curve= 0 ,0
Exp/Cntr=0.3,0.1

Type RM Length L Ch R = 1 ,4275.5  ,991.6,997.4,1003.1
XS GIS Cut Line= 2
     1930601.475      161140.291      1930442.26      159565.441
#Sta/Elev= 30
       0 2256.47    19.9 2241.35    39.8 2223.68    49.8 2222.46    69.7 2204.17
    79.6 2196.71   139.4 2156.57   149.3 2154.84   159.3 2149.64   238.9 2101.98
   248.9 2099.96   258.8 2096.01   308.6 2068.44   318.6 2064.36   328.5 2062.63
   338.5 2062.35   527.6 2058.84   826.3  2057.9   880.1 2057.94   895.1 2058.02
  1025.4 2063.98  1244.4 2069.59  1363.9 2076.37  1393.7 2083.86  1433.6 2086.18
  1443.5 2089.24  1473.4  2102.3  1513.2 2121.16  1533.1 2124.84  1582.9  2142.3
#Mann= 3 , 0 , 0
       0     .06       0   880.1    .045       0   895.1     .06       0
Bank Sta=880.1,895.1
XS Rating Curve= 0 ,0
Exp/Cntr=0.3,0.1