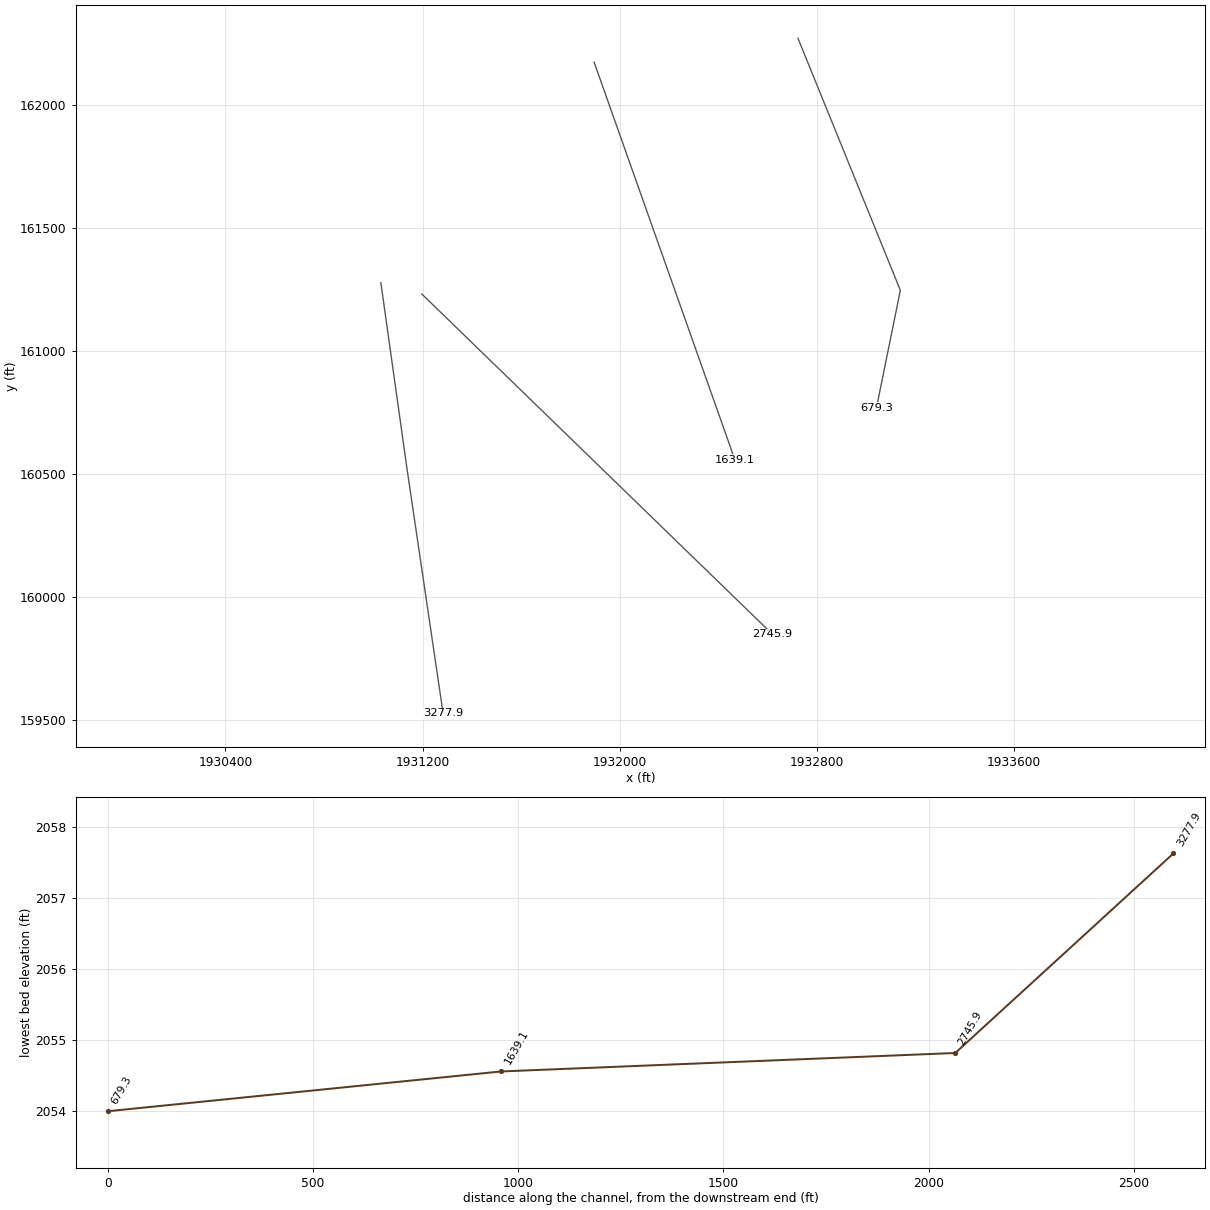
HEC-RAS study RchCrk.prj: RchCrk

--- RchCrk.g01 (geometry) --- (continued)

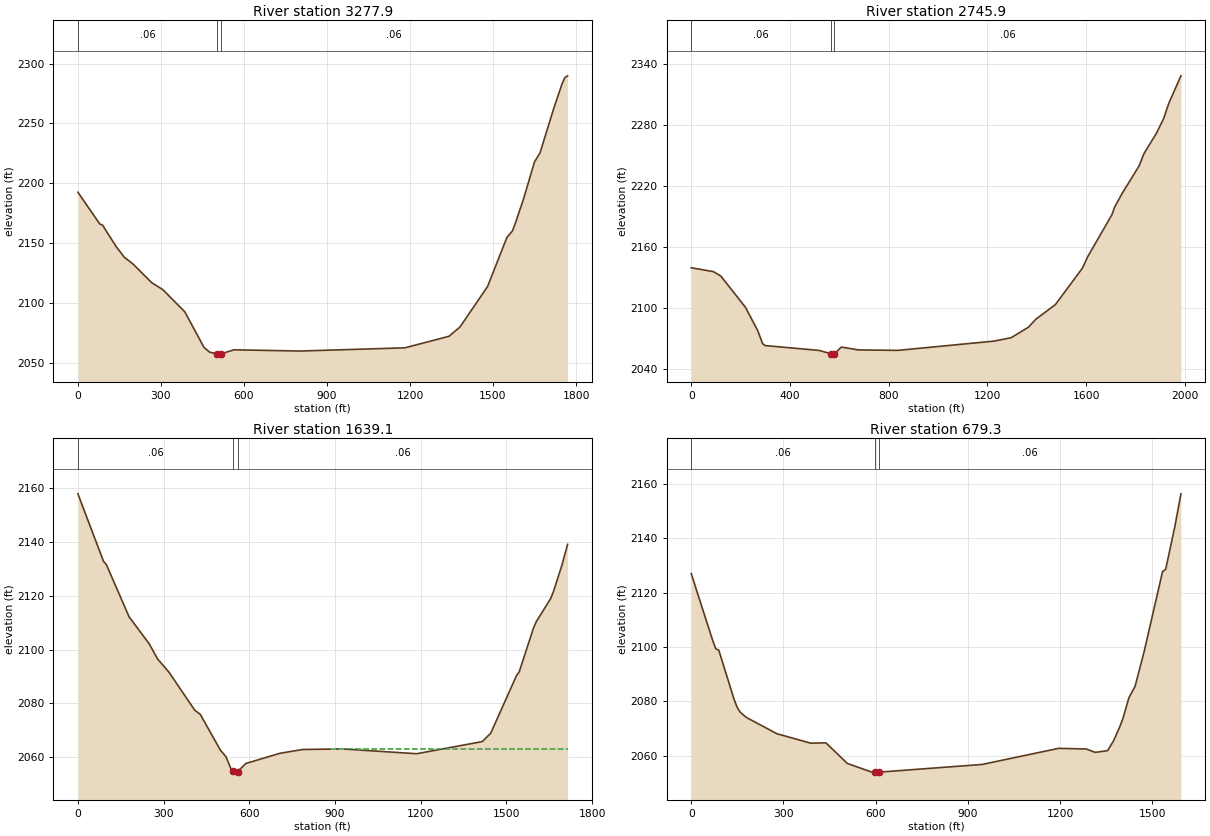
Type RM Length L Ch R = 1 ,3277.9  ,516.5,531.5,546.4
XS GIS Cut Line= 3
     1931030.665       161278.74     1931137.963      160513.812
     1931283.334      159527.367
#Sta/Elev= 30
       0 2192.65    79.2 2166.12    89.1 2165.23   138.6 2147.17   168.4 2138.24
   198.1    2133   267.4  2117.1     307  2111.4   386.2 2092.96   455.5 2063.34
   475.3 2059.36   502.1  2057.8     505 2057.63   517.1 2057.88   564.5 2061.25
   802.3  2060.2  1181.2 2062.88  1340.8  2072.5  1380.6 2080.23  1480.4 2114.06
  1550.2 2154.93  1570.1 2160.31  1580.1 2166.34    1610 2186.82  1649.9  2217.9
  1669.8 2225.41  1719.7 2262.69  1749.6 2283.12  1759.5 2288.15  1769.5 2289.72
#Mann= 3 , 0 , 0
       0     .06       0   502.1    .045       0   517.1     .06       0
Bank Sta=502.1,517.1
XS Rating Curve= 0 ,0
Exp/Cntr=0.3,0.1

Type RM Length L Ch R = 1 ,2745.9  ,1117,1106.7,1096.3
XS GIS Cut Line= 2
     1931196.896      161232.537     1932619.361       159849.26
#Sta/Elev= 30
       0 2139.81    89.7 2135.99   119.6 2131.73   219.4 2101.01   269.2 2078.07
   289.2 2065.12   299.1 2063.26   518.5 2058.45   564.7 2055.32   578.3 2054.82
   579.7 2055.05   608.2 2061.75     678 2058.95   837.5 2058.52  1226.4 2067.61
  1296.2 2070.98    1366 2081.24  1395.9  2089.1  1475.6 2103.56  1585.3 2139.51
  1605.3 2150.16    1705 2192.21    1715 2199.22  1744.9 2212.52  1814.6 2239.98
  1834.6 2252.18  1884.4 2271.95  1914.4 2286.69  1934.3 2301.15  1984.2 2328.66
#Mann= 3 , 0 , 0
       0     .06       0   564.7    .045       0   579.7     .06       0
Bank Sta=564.7,579.7
XS Rating Curve= 0 ,0
Exp/Cntr=0.3,0.1

Type RM Length L Ch R = 1 ,1639.1  ,947.6,958.2,1012.9
XS GIS Cut Line= 2
     1931895.968      162175.193     1932467.068      160558.808
#Sta/Elev= 30
       0  2157.7    89.7 2132.68    99.7 2131.48   179.4 2112.09   249.2 2102.19
   279.1 2096.48   318.9  2091.6   408.6 2077.57   428.6 2075.95   498.4 2062.79
   518.3 2060.28   538.2 2055.21   543.8 2054.85   548.2 2054.56   558.8 2054.74
     588 2057.77   707.6 2061.55   787.4 2062.96   926.9 2063.15  1186.1 2061.38
  1415.3 2065.87  1445.2 2068.98  1534.9  2090.2  1544.9 2091.71  1594.7 2107.87
  1604.7 2110.33  1654.5 2118.79  1664.5 2121.37  1694.4 2131.24  1714.3 2138.96
#Mann= 3 , 0 , 0
       0     .06       0   543.8    .045       0   558.8     .06       0
#XS Ineff= 2 , 0
                          886.96         2063.25
Permanent Ineff=
       F       F
Bank Sta=543.8,558.8
XS Rating Curve= 0 ,0
Exp/Cntr=0.3,0.1

Type RM Length L Ch R = 1 ,679.3   ,682.8,679.9,626.7
XS GIS Cut Line= 3
     1932723.197      162272.107     1933138.543      161247.589
     1933041.629      160769.942
#Sta/Elev= 30
       0 2126.98    69.7 2102.42    79.7 2099.37    89.6 2098.85   139.4 2080.74
   149.4 2077.83   159.4 2076.03   179.3  2074.1   278.9 2068.11   388.4 2064.65
   438.2 2064.76   507.9 2057.18   587.6    2054   596.6    2054   611.6    2054
   946.2 2056.82    1195 2062.74  1284.6 2062.51  1314.4 2061.27  1354.2 2061.88
  1374.1 2065.58    1394 2070.68  1403.9 2073.63  1423.8 2081.37  1443.7 2085.52
  1473.5 2098.43  1533.2 2127.76  1543.2 2128.51    1573 2144.18  1592.9  2156.3
#Mann= 3 , 0 , 0
       0     .06       0   596.6    .045       0   611.6     .06       0
Bank Sta=596.6,611.6
XS Rating Curve= 0 ,0
Exp/Cntr=0.3,0.1

Chan Stop Cuts=-1
Use User Specified Reach Order=0
Composite Channel Slope=5